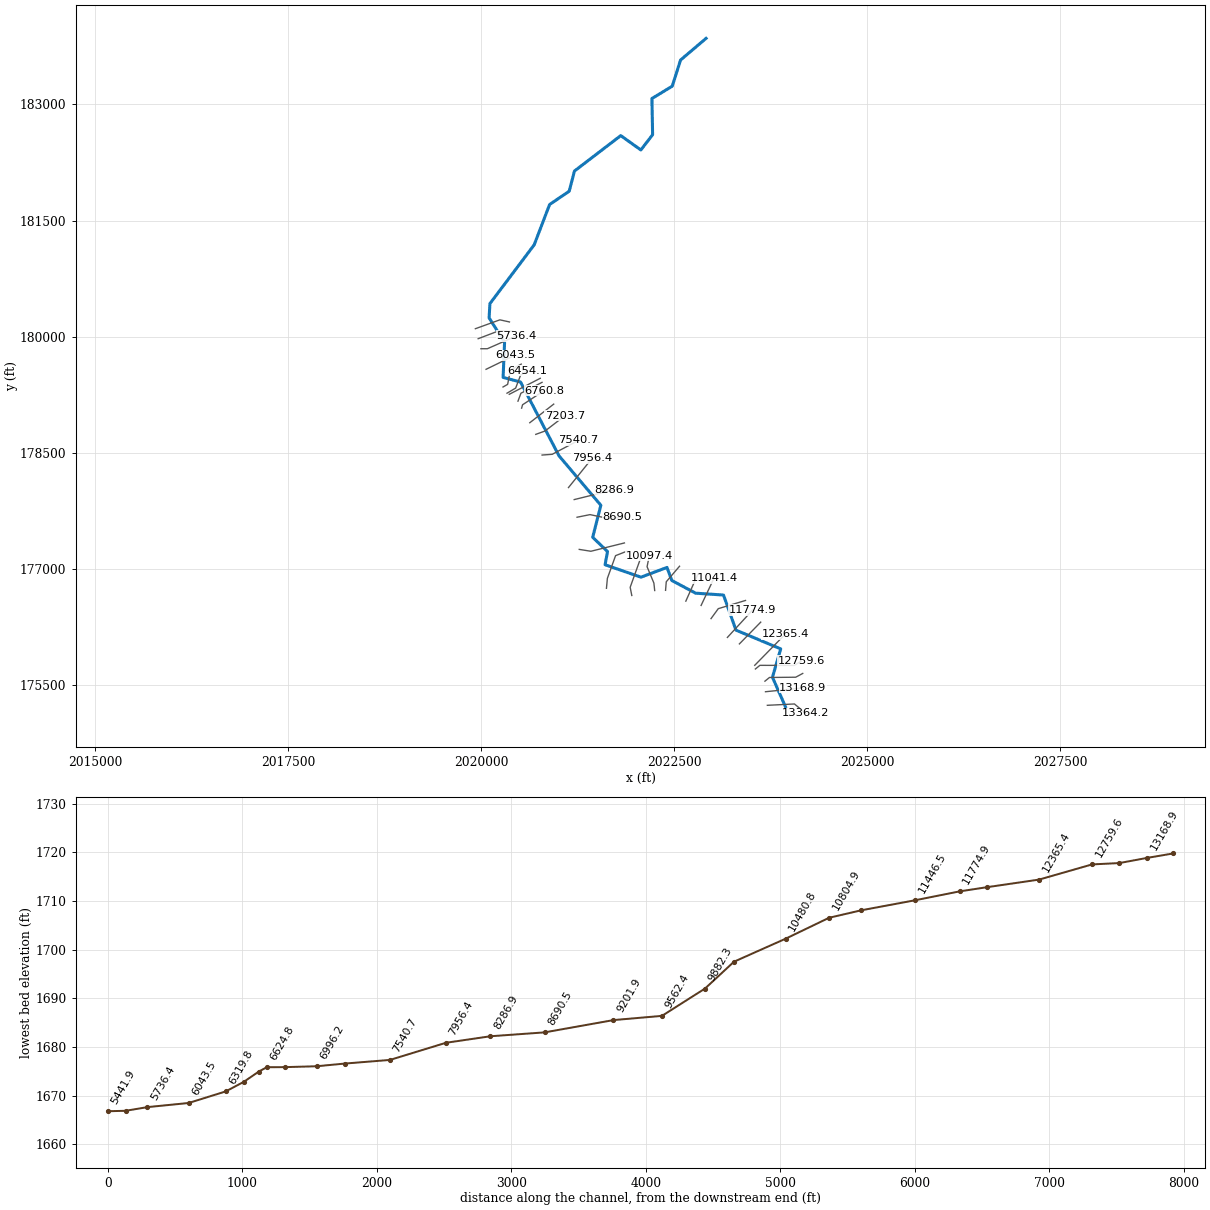
--- STNKLKCK.prj (project) ---

Proj Title=STNKLKCK
Current Plan=p01
Default Exp/Contr=0,0
English Units
Geom File=g01
Flow File=f01
Plan File=p01
BEGIN DESCRIPTION:
END DESCRIPTION:
DSS Export Rating Curves= 0
DSS Export Rating Curve Sorted= 0
DSS Export Volume Flow Curves= 0
DXF Filename=..\STNKLKCK.
DXF OffsetX= 0
DXF OffsetY= 0
DXF ScaleX= 0
DXF ScaleY= 0

--- STNKLKCK.p01 (plan) ---

Plan Title=Floodplain
Program Version=4.00
Geom File=g01
Flow File=f01
K Sum by GR=0
Std Step Tol=0.01
Critical Tol=0.01
Num of Std Step Trials=20
Max Error Tol=0.3
Flow Tol Ratio=0.001
Split Flow NTrial=30
Split Flow Tol=0.02
Split Flow Ratio=0.02
Log Output Level=0
Friction Slope Method=1
Unsteady Friction Slope Method=2
Unsteady Bridges Friction Slope Method=1
Global Log Level=0
CheckData=False
Run HTab=0
Run UNet=0
Run PostProcess=0
UNET Theta=0
UNET Theta Warmup=0
UNET ZTol=0
UNET ZSATol=0
UNET MxIter=0
UNET MaxInSteps=0
UNET DtIC=0
UNET DtMin=0
UNET MaxCRTS=0
UNET WFStab=0
UNET SFStab=0
UNET WFX=0
UNET SFX=0
UNET DSS MLevel=0
UNET DZMax Abort=0
UNET Convert EG Bridges=0
UNET Use Existing IB Tables=0
UNET Froude Limit=0
UNET Froude Power=0
Write IC File=0
Echo Input=False
Echo Output=False
Write Detailed=0

--- STNKLKCK.f01 (steady flow) ---

Flow Title=NFF Regression Equation
Program Version=4.10
Number of Profiles= 1
Profile Names=P100yr
River Rch & RM=STNKLKCK,Main            ,13364.2
796.1914
River Rch & RM=STNKLKCK,Main            ,9201.9
 830.774
River Rch & RM=STNKLKCK,Main            ,8690.5
1019.196
River Rch & RM=STNKLKCK,Main            ,7540.7
1083.507
River Rch & RM=STNKLKCK,Main            ,4094.3
1165.019
Boundary for River Rch & Prof#=STNKLKCK,Main            , 1
Up Type= 0
Dn Type= 1
Dn Known WS=1606.9
DSS Import GetInterval= 0
DSS Import GetPeak= 0
DSS Import FillOption= 0

--- STNKLKCK.g01 (geometry) ---

Geom Title=USGS 10m DEM
Program Version=4.10

River Reach=STNKLKCK        ,Main
Reach XY= 30
     2023939.303       175222.31     2023771.298      175601.184
     2023878.243      175967.851     2023299.076      176210.212
     2023137.626      176663.515     2022776.854      176687.295
     2022468.326      176851.471      2022406.02      177019.934
     2022069.215      176894.239     2021604.785      177054.596
     2021636.035      177225.429     2021444.119      177409.132
      2021549.77      177822.712     2021007.833      178461.819
     2020510.187      179414.378     2020284.493      179474.101
     2020303.352      179927.838     2020103.243      180242.851
     2020113.659      180426.878      2020686.53      181186.143
     2020886.576      181707.434      2021140.06      181878.785
     2021208.104      182139.379     2021807.409      182597.017
     2022067.826      182411.601     2022219.909      182608.823
     2022210.882      183076.184     2022474.076      183235.212
     2022581.697      183573.304     2022912.303      183853.394

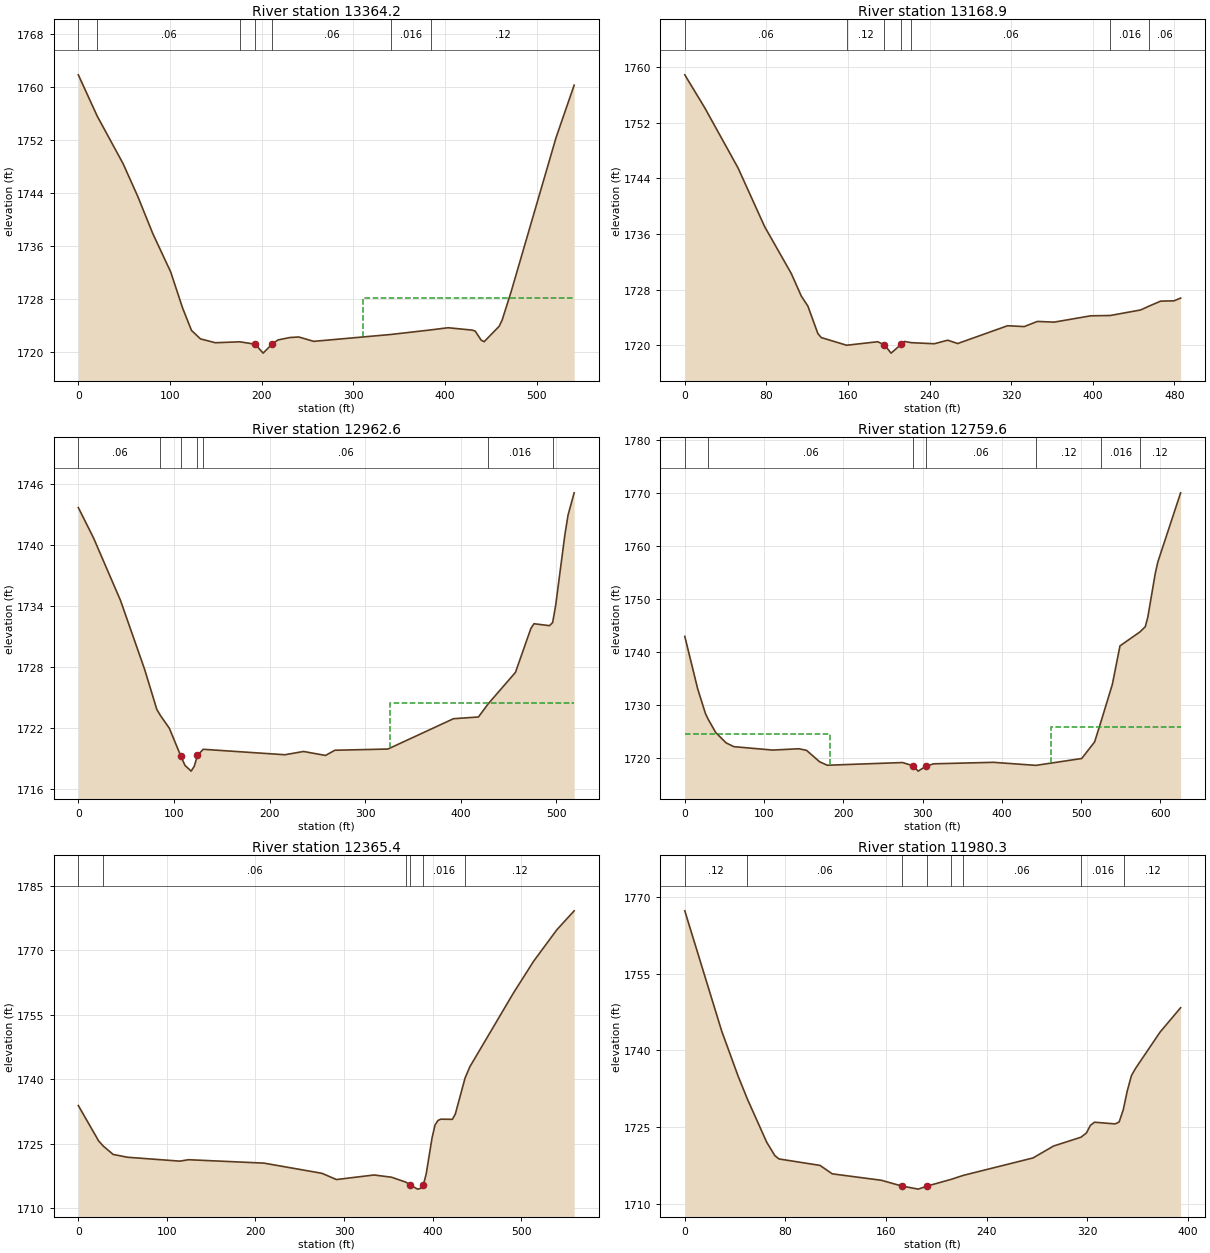
Type RM Length L Ch R = 1 ,13364.2 ,193,195.2,197.1
XS GIS Cut Line= 3
      2023705.48       175239.26     2024056.174      175256.622
     2024202.008      175135.094
#Sta/Elev= 30
       0 1761.86   20.661755.604    48.8 1748.44      65 1743.43    81.3 1737.84
   100.8 1732.05   113.8 1726.59   123.5 1723.21   133.3 1721.93   149.6 1721.35
  176.021721.493  193.09 1721.13   201.6 1719.78   211.3 1721.13   217.8 1721.77
   230.8 1722.14   240.6 1722.22   256.8 1721.56  341.061722.601  384.871723.296
   403.5 1723.62   429.7 1723.26     433 1723.12   439.5 1721.75   442.8 1721.51
   459.1 1723.83   462.4 1724.77   472.2 1729.05   521.3 1752.39     541  1760.3
#Mann= 7 ,-1 , 0
       0     .12       0   20.66     .06       0  176.02     .12       0
  193.09    .045       0   211.3     .06       0  341.06    .016       0
  384.87     .12       0
#XS Ineff= 2 , 0
                          310.23         1728.11
Permanent Ineff=
       F       F
Bank Sta=193.09,211.3
XS Rating Curve= 0 ,0
Exp/Cntr=0.3,0.1

Type RM Length L Ch R = 1 ,13168.9 ,208.5,206.3,202.9
XS GIS Cut Line= 2
     2023681.174      175414.608     2024164.826      175463.826
#Sta/Elev= 30
       0  1758.9    19.6 1754.15    52.2 1745.51    78.3 1737.06   104.4 1730.32
   114.2 1727.08   120.7 1725.63   130.5 1721.67   133.8  1721.1  158.671719.995
   189.2  1720.5   195.8 1720.03   202.3 1718.86   212.1 1720.12   215.3 1720.54
  222.231720.364   244.7 1720.21   257.8 1720.72   267.6 1720.24   316.5  1722.8
   332.8 1722.68   345.8 1723.42   362.2 1723.32   398.1 1724.23  417.051724.271
     447 1725.07  455.191725.618   466.6 1726.34   479.6 1726.38   486.2 1726.78
#Mann= 7 ,-1 , 0
       0     .06       0  158.67     .12       0   195.8    .045       0
   212.1     .12       0  222.23     .06       0  417.05    .016       0
  455.19     .06       0
Bank Sta=195.8,212.1
XS Rating Curve= 0 ,0
Exp/Cntr=0.3,0.1

Type RM Length L Ch R = 1 ,12962.6 ,198.2,203.1,203.7
XS GIS Cut Line= 4
     2023674.158      175551.066     2023732.751      175598.809
     2024072.378      175602.064     2024163.524      175650.892
#Sta/Elev= 30
       0 1743.69    15.8 1740.73    44.1 1734.57    69.3 1727.81    82.1 1723.86
   85.881723.266    95.2 1722.01   107.3 1719.26   111.5 1718.37     118  1717.8
   121.3 1718.29   124.6 1719.34  130.591719.945     216 1719.41   235.6 1719.73
   258.5 1719.34   268.3 1719.85   323.8 1719.97   392.4 1722.95   418.5 1723.12
  428.561724.398   457.2  1727.5   473.4 1731.83   476.6 1732.28   492.8 1732.09
  496.111732.398   499.2 1734.04   508.9 1741.02   512.2 1742.95   518.6 1745.14
#Mann= 7 ,-1 , 0
       0     .06       0   85.88     .12       0   107.3    .045       0
   124.6     .12       0  130.59     .06       0  428.56    .016       0
  496.11     .12       0
#XS Ineff= 2 , 0
                          325.57         1724.54
Permanent Ineff=
       F       F
Bank Sta=107.3,124.6
XS Rating Curve= 0 ,0
Exp/Cntr=0.3,0.1

Type RM Length L Ch R = 1 ,12759.6 ,375.1,394.2,409.4
XS GIS Cut Line= 4
      2023550.46      175708.401     2023608.836      175755.493
     2024054.149      175754.191     2024142.908      175810.615
#Sta/Elev= 30
       0 1742.92    16.3 1733.02    26.1 1728.36   29.391727.333    39.1 1724.78
    52.2 1722.84      62 1722.13     111 1721.49   143.8 1721.74   153.6 1721.44
     170 1719.29   179.8 1718.63   274.7 1719.14   287.8 1718.54   294.4 1717.52
   304.2 1718.45     314  1718.9   389.3 1719.18  442.921718.604   500.7  1719.9
     517 1723.03  525.621727.136   539.4  1733.9     549 1741.14  574.151743.767
   580.9 1744.75   584.1 1746.54   593.6 1754.88   596.8 1756.98   625.5    1770
#Mann= 7 ,-1 , 0
       0     .12       0   29.39     .06       0   287.8    .045       0
   304.2     .06       0  442.92     .12       0  525.62    .016       0
  574.15     .12       0
#XS Ineff= 2 , 0
          182.95 1724.52  461.36         1725.75
Permanent Ineff=
       F       F
Bank Sta=287.8,304.2
XS Rating Curve= 0 ,0
Exp/Cntr=0.3,0.1

Type RM Length L Ch R = 1 ,12365.4 ,387.9,385.1,378.1
XS GIS Cut Line= 2
     2023541.851      175755.754     2023934.213      176155.059
#Sta/Elev= 30
       0 1733.84    22.9 1725.62   28.131724.417    39.3 1722.47    55.6 1721.81
   114.6 1720.91   124.4 1721.24   209.5 1720.45     275 1718.08   291.4 1716.63
   333.9 1717.69   353.6 1717.17  369.991716.007     374 1715.46     383  1714.4
   386.3 1714.57   389.6 1715.42   392.8 1717.99   399.4 1726.37   402.7 1729.29
     406 1730.36   409.2 1730.67   422.3 1730.63   425.6 1731.84  436.611740.228
     442 1742.84   491.1 1759.96     514 1767.39   540.2  1774.7   559.8 1779.12
#Mann= 6 ,-1 , 0
       0     .12       0   28.13     .06       0  369.99     .12       0
     374    .045       0   389.6    .016       0  436.61     .12       0
Bank Sta=374,389.6
XS Rating Curve= 0 ,0
Exp/Cntr=0.3,0.1

Type RM Length L Ch R = 1 ,11980.3 ,198.2,205.4,212.8
XS GIS Cut Line= 2
     2023343.501      176032.229     2023619.542      176313.479
#Sta/Elev= 30
       0 1767.29    29.3 1743.79    42.3 1735.01   49.781730.449    65.1 1722.03
    71.6  1719.4    74.9 1718.75   107.5 1717.49   117.2 1715.84   156.3 1714.58
   172.6 1713.45   185.6 1712.85   192.9 1713.47  211.831714.769  221.231715.532
   276.8 1718.95   293.1 1721.28  314.911723.007   319.2 1723.83   322.4 1725.33
   325.7 1725.94     342 1725.61   345.2 1725.97   348.5 1728.36  349.291729.276
   351.7 1732.07     355 1735.05   358.3 1736.48   377.8 1743.58   394.1 1748.34
#Mann= 8 ,-1 , 0
       0     .12       0   49.78     .06       0   172.6    .045       0
   192.9     .06       0  211.83     .12       0  221.23     .06       0
  314.91    .016       0  349.29     .12       0
Bank Sta=172.6,192.9
XS Rating Curve= 0 ,0
Exp/Cntr=0.3,0.1

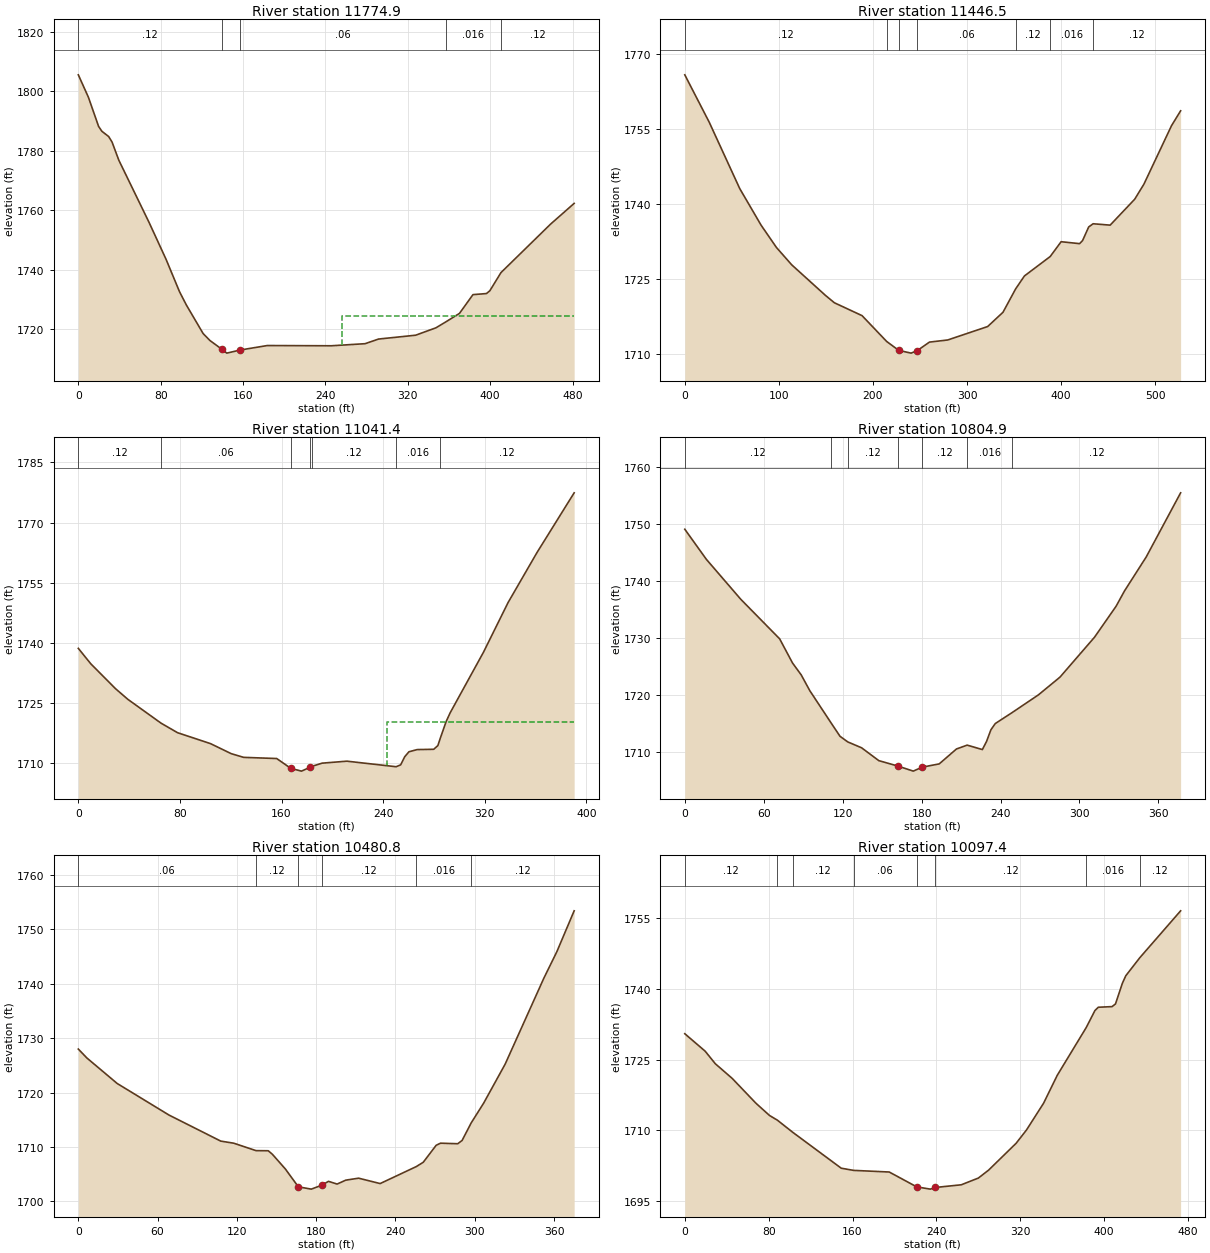
Type RM Length L Ch R = 1 ,11774.9 ,339.5,328.5,315.9
XS GIS Cut Line= 2
     2023188.119      176115.997     2023514.508      176470.163
#Sta/Elev= 30
       0 1805.52     9.8 1797.98    19.7 1788.17    22.9 1786.54    29.5 1784.77
    32.8 1782.89    39.3 1776.85    68.8 1755.85    85.2 1743.52    98.3 1732.62
   104.8 1728.24   121.2 1718.57   127.8 1716.23   139.5 1713.26   144.2 1711.98
   157.3 1713.03   183.5 1714.53   245.7 1714.45   278.5 1715.15   291.6 1716.71
   327.6    1718   347.3 1720.48  356.881722.468   370.2 1725.33   383.3 1731.64
   396.4    1732   399.7 1732.94  410.521739.046   458.7 1755.34   481.6 1762.31
#Mann= 5 ,-1 , 0
       0     .12       0   139.5    .045       0   157.3     .06       0
  356.88    .016       0  410.52     .12       0
#XS Ineff= 2 , 0
                          256.39         1724.46
Permanent Ineff=
       F       F
Bank Sta=139.5,157.3
XS Rating Curve= 0 ,0
Exp/Cntr=0.3,0.1

Type RM Length L Ch R = 1 ,11446.5 ,384.7,405.1,421.4
XS GIS Cut Line= 3
     2022976.313      176359.052     2023070.063      176487.524
     2023422.494      176593.427
#Sta/Elev= 30
       0 1765.77      26 1756.29    58.4 1743.04    81.1 1735.73    97.4 1731.28
   113.6 1727.82   149.3 1721.74     159 1720.23   188.4 1717.66  214.541712.505
   227.4 1710.72   240.5 1710.17     247 1710.66     260 1712.37   279.5  1712.8
   321.9 1715.48   338.2 1718.33  351.651723.007     361 1725.59  388.371729.467
     400 1732.43   419.6 1732.04   422.8 1732.66   429.3 1735.38  433.991736.015
   452.1 1735.74   478.2 1740.92     488 1743.93   517.3  1755.6     527 1758.58
#Mann= 7 ,-1 , 0
       0     .12       0  214.54     .06       0   227.4    .045       0
     247     .06       0  351.65     .12       0  388.37    .016       0
  433.99     .12       0
Bank Sta=227.4,247
XS Rating Curve= 0 ,0
Exp/Cntr=0.3,0.1

Type RM Length L Ch R = 1 ,11041.4 ,235.6,236.5,235.2
XS GIS Cut Line= 2
     2022847.557      176529.127     2023015.086      176881.795
#Sta/Elev= 30
       0 1738.67     9.8 1734.83    29.3 1728.62      39 1725.97   65.111720.038
    78.1 1717.66   104.1 1714.93   120.4 1712.43   130.2 1711.51   156.2 1711.22
   167.3 1708.77   175.7 1708.08   182.3 1709.02  183.971709.276     192 1710.07
   211.5 1710.56  250.241709.175   253.8 1709.65     257 1711.67   260.3  1712.9
   266.8 1713.45   279.8 1713.52   283.1 1714.45  284.851716.145   289.6 1720.43
   292.8 1722.63   318.9 1737.65   338.4  1750.1   361.2 1762.58   390.4 1777.43
#Mann= 7 ,-1 , 0
       0     .12       0   65.11     .06       0   167.3    .045       0
   182.3     .06       0  183.97     .12       0  250.24    .016       0
  284.85     .12       0
#XS Ineff= 2 , 0
                          243.18         1720.38
Permanent Ineff=
       F       F
Bank Sta=167.3,182.3
XS Rating Curve= 0 ,0
Exp/Cntr=0.3,0.1

Type RM Length L Ch R = 1 ,10804.9 ,330.2,324.1,318.7
XS GIS Cut Line= 2
     2022649.924      176584.747     2022804.149       176928.67
#Sta/Elev= 30
       0 1749.07    16.4 1743.78    42.6 1736.75    72.1 1729.81    81.9 1725.56
    88.5 1723.47      95 1720.71  111.291715.003     118 1712.68  123.861711.697
   134.4 1710.66   147.5  1708.4     162 1707.45   173.7 1706.56   180.3 1707.25
   193.4 1707.83   206.5 1710.45  214.64 1711.13   226.2 1710.35   229.4 1711.79
   232.7 1713.83     236 1714.92     2491716.876   268.8 1719.96   285.2 1723.08
   311.4 1730.08   327.8 1735.52   334.3 1738.25   350.7 1744.18   376.9 1755.47
#Mann= 7 ,-1 , 0
       0     .12       0  111.29     .06       0  123.86     .12       0
     162    .045       0   180.3     .12       0  214.64    .016       0
     249     .12       0
Bank Sta=162,180.3
XS Rating Curve= 0 ,0
Exp/Cntr=0.3,0.1

Type RM Length L Ch R = 1 ,10480.8 ,354.6,383.3,407.5
XS GIS Cut Line= 3
     2022387.482      176724.243     2022396.597       176834.92
     2022568.472      177035.441
#Sta/Elev= 30
       0 1727.98     6.5 1726.34    29.4 1721.66    68.6 1715.86   107.8 1711.07
   117.6 1710.69  134.481709.321   143.7  1709.3   146.9 1708.64   156.7 1705.94
   166.5 1702.67   176.3 1702.25   184.1 1702.96   189.3 1703.68   195.8 1703.18
   202.4  1703.9   212.1 1704.26   228.4 1703.27  255.691706.386     261 1707.18
   270.8 1710.31   274.1 1710.69   287.1 1710.59   290.4 1711.19  297.361714.448
   306.7 1718.04     323 1725.22   352.3 1741.02   362.1 1745.87   375.2 1753.38
#Mann= 6 ,-1 , 0
       0     .06       0  134.48     .12       0   166.5    .045       0
   184.1     .12       0  255.69    .016       0  297.36     .12       0
Bank Sta=166.5,184.1
XS Rating Curve= 0 ,0
Exp/Cntr=0.3,0.1

Type RM Length L Ch R = 1 ,10097.4 ,231.4,215.1,197.9
XS GIS Cut Line= 4
     2022246.857      176721.639     2022236.441      176817.993
     2022148.188      177029.191     2022177.702      177173.288
#Sta/Elev= 30
       0 1730.51    19.4 1726.81    29.1 1724.14    45.2 1721.03    67.8 1715.77
    80.8 1713.16   88.251712.169  103.141709.561   149.2 1701.97     1611701.508
     195 1701.16   221.2 1698.01   234.2 1697.53     239 1697.88   263.7 1698.45
     280 1699.88   289.8 1701.57     316 1707.26   325.8 1710.05   342.2 1715.76
   355.2 1721.67  382.84 1731.81   391.2 1735.44   394.4 1736.13   407.5 1736.26
   410.8 1736.84   417.3 1741.19   420.6 1742.81  433.93 1746.63   472.9 1756.59
#Mann= 8 ,-1 , 0
       0     .12       0   88.25     .06       0  103.14     .12       0
     161     .06       0   221.2    .045       0     239     .12       0
  382.84    .016       0  433.93     .12       0
Bank Sta=221.2,239
XS Rating Curve= 0 ,0
Exp/Cntr=0.3,0.1

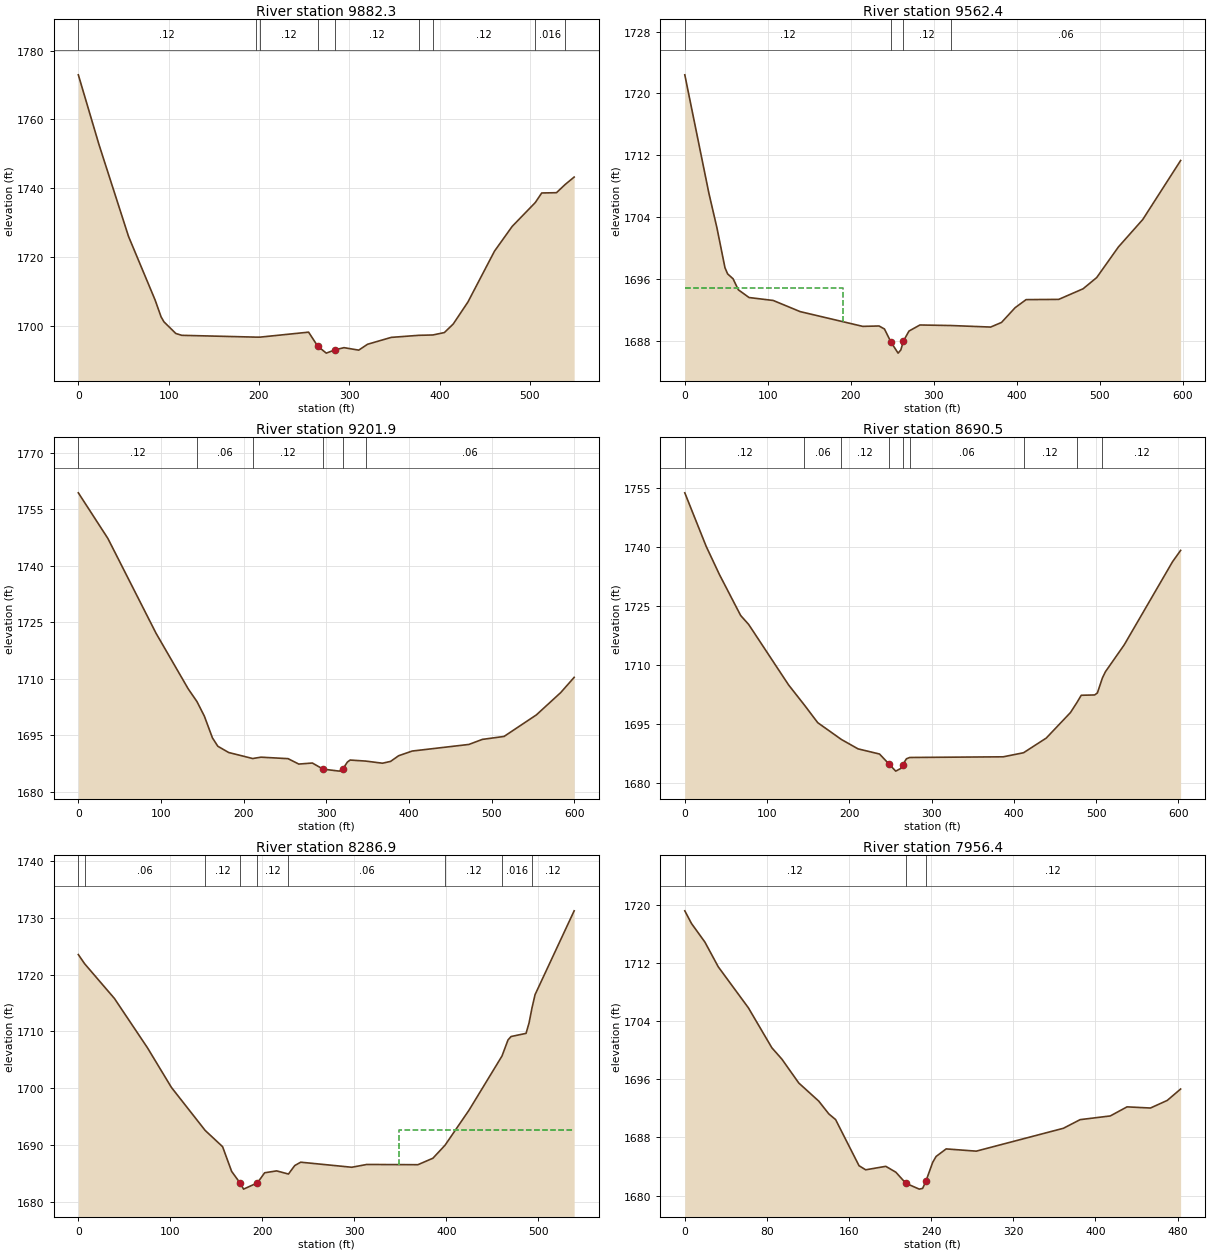
Type RM Length L Ch R = 1 ,9882.3  ,319.6,319.9,319.5
XS GIS Cut Line= 3
     2021950.272      176657.663     2021929.438      176763.566
     2022078.744      177178.497
#Sta/Elev= 30
       0 1772.98    22.9 1752.66    55.6 1725.95      85 1707.47    91.6 1702.58
    94.8 1701.12   107.9 1697.74   114.5  1697.2  196.541696.675  201.131696.673
   254.9 1698.12   265.2 1693.98   274.5 1692.02   284.3 1692.99   294.1 1693.61
   310.4 1692.89   320.2  1694.6   346.4  1696.6  376.93  1697.2  392.49  1697.3
   405.2    1698     415 1700.48   431.3 1706.89   460.7 1721.68   480.3 1728.89
  505.881735.829     513 1738.61   529.3 1738.69     5391741.092   548.9 1743.24
#Mann= 9 ,-1 , 0
       0     .12       0  196.54     .06       0  201.13     .12       0
   265.2    .045       0   284.3     .12       0  376.93     .06       0
  392.49     .12       0  505.88    .016       0     539     .12       0
Bank Sta=265.2,284.3
XS Rating Curve= 0 ,0
Exp/Cntr=0.3,0.1

Type RM Length L Ch R = 1 ,9562.4  ,381.7,360.6,334.5
XS GIS Cut Line= 4
     2021622.291      176750.719     2021634.444      176879.191
     2021740.347       177172.16      2021886.18      177229.451
#Sta/Elev= 30
       0  1722.4      29  1707.1    38.7 1702.62    48.4 1697.45    51.6 1696.65
    58.1 1696.03    64.5  1694.6    77.4  1693.6   106.5 1693.22   138.9 1691.78
   214.3 1689.87     234 1689.92   240.5 1689.53   248.3 1687.84   256.9 1686.41
   260.2 1686.82   263.3 1687.97     270 1689.26   283.2 1690.05  321.041689.978
   368.4 1689.78   381.5 1690.38   397.9 1692.29   411.1 1693.33   450.4 1693.36
   479.7 1694.73   496.1 1696.18   522.2 1700.13   551.6 1703.69   597.2 1711.32
#Mann= 4 ,-1 , 0
       0     .12       0   248.3    .045       0   263.3     .12       0
  321.04     .06       0
#XS Ineff= 2 , 0
          190.91 1694.78
Permanent Ineff=
       F       F
Bank Sta=248.3,263.3
XS Rating Curve= 0 ,0
Exp/Cntr=0.3,0.1

Type RM Length L Ch R = 1 ,9201.9  ,521.7,511.3,499.2
XS GIS Cut Line= 3
     2021270.295      177252.889     2021420.758      177228.844
      2021854.93      177336.222
#Sta/Elev= 30
       0 1759.38    35.7 1747.29      94 1722.11   132.9 1707.36  143.451704.003
   152.4 1700.13   162.2 1694.35   168.7 1692.14   181.8 1690.48  210.851688.882
   220.9 1689.24   253.6 1688.85   266.6 1687.41     283 1687.69     296 1686.07
   315.6 1685.54  319.78  1686.1   325.4 1687.95   328.7 1688.48  347.511688.205
   367.8 1687.64   377.6 1688.12   387.4 1689.63   403.8 1690.87   472.3 1692.62
   488.6 1693.96   514.8 1694.74   553.9 1700.46   583.3 1706.37   599.6 1710.42
#Mann= 6 ,-1 , 0
       0     .12       0  143.45     .06       0  210.85     .12       0
     296    .045       0  319.78     .12       0  347.51     .06       0
Bank Sta=296,319.78
XS Rating Curve= 0 ,0
Exp/Cntr=0.3,0.1

Type RM Length L Ch R = 1 ,8690.5  ,397.9,403.6,414.3
XS GIS Cut Line= 4
     2021241.649      177668.254     2021409.618      177702.108
     2021668.732       177647.42     2021832.795      177676.066
#Sta/Elev= 30
       0 1753.79    25.9 1740.23      42 1733.05    67.9  1722.6    77.6 1720.33
   126.1 1704.96  145.291699.849   161.6 1695.34  190.251691.081   210.6 1688.68
   236.7 1687.37  248.52 1684.76   256.4 1683.02   262.9 1683.74   264.9 1684.63
   269.4 1686.16  273.441686.491   387.1 1686.66  411.791687.697   439.4 1691.43
   468.8 1697.92  476.63 1700.46   481.9 1702.31   498.2 1702.39   501.5  1702.9
  507.621706.711   511.3  1708.3   534.1 1715.12   592.9 1736.28   602.7 1739.15
#Mann= 9 ,-1 , 0
       0     .12       0  145.29     .06       0  190.25     .12       0
  248.52    .045       0   264.9     .12       0  273.44     .06       0
  411.79     .12       0  476.63    .016       0  507.62     .12       0
Bank Sta=248.52,264.9
XS Rating Curve= 0 ,0
Exp/Cntr=0.3,0.1

Type RM Length L Ch R = 1 ,8286.9  ,315.6,330.5,344.5
XS GIS Cut Line= 2
      2021205.11      177896.261      2021728.42      178024.968
#Sta/Elev= 30
       0 1723.51    6.871721.889    39.2 1715.79    75.1 1707.11   101.2 1700.12
  137.861692.552   156.8 1689.69   166.6 1685.35  175.65 1683.33   179.6 1682.22
   194.7 1683.33   202.5  1685.1   215.6 1685.43  228.381684.875   235.2 1686.37
   241.7 1686.96   297.2 1686.07   313.5 1686.56   369.1 1686.52   385.4 1687.66
  398.531689.945   424.6 1696.11  460.481705.655     467 1708.48   470.3 1709.08
   486.6 1709.64   489.9 1711.49  493.051714.105   496.4 1716.45   538.9 1731.21
#Mann= 9 ,-1 , 0
       0     .12       0    6.87     .06       0  137.86     .12       0
  175.65    .045       0   194.7     .12       0  228.38     .06       0
  398.53     .12       0  460.48    .016       0  493.05     .12       0
#XS Ineff= 2 , 0
                          348.58         1692.69
Permanent Ineff=
       F       F
Bank Sta=175.65,194.7
XS Rating Curve= 0 ,0
Exp/Cntr=0.3,0.1

Type RM Length L Ch R = 1 ,7956.4  ,424.1,415.7,406.1
XS GIS Cut Line= 2
       2021130.8      178051.542     2021434.674      178426.979
#Sta/Elev= 30
       0 1719.21     6.5 1717.47    19.6  1714.9    32.6  1711.5      62 1705.84
    84.8 1700.35    94.6 1698.78     111  1695.5   130.5    1693   140.3 1691.24
   146.9 1690.46   169.7 1684.11   176.2 1683.54   195.8 1684.02   205.6 1683.21
   215.3 1681.69   228.4 1680.88   231.7 1680.98     235 1682.03   241.5 1684.57
   244.8 1685.38   254.6 1686.42   283.9 1686.11   368.8 1689.26   385.1 1690.45
   414.5 1690.96   430.8 1692.21   453.6 1692.05     470  1693.1     483 1694.67
#Mann= 3 ,-1 , 0
       0     .12       0   215.3    .045       0     235     .12       0
Bank Sta=215.3,235
XS Rating Curve= 0 ,0
Exp/Cntr=0.3,0.1

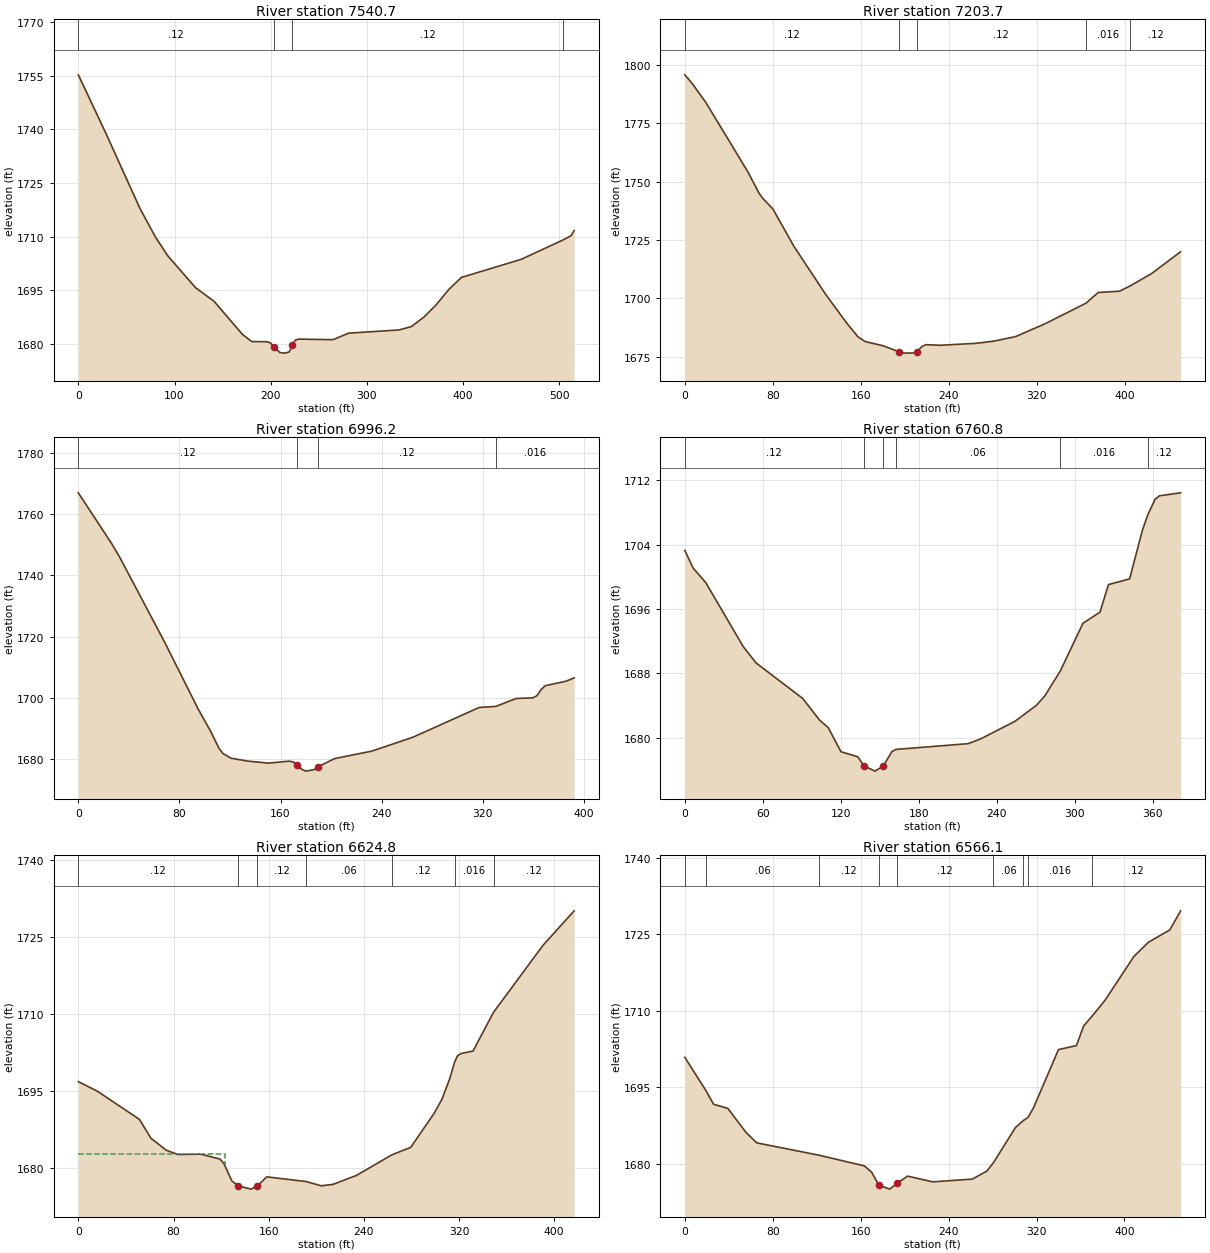
Type RM Length L Ch R = 1 ,7540.7  ,331.8,337,339.4
XS GIS Cut Line= 3
     2020788.883      178471.463     2020919.901      178481.034
     2021259.519      178660.617
#Sta/Elev= 30
       0 1755.26    28.8 1738.81    64.1 1717.85    80.1  1709.9    92.9 1704.63
   121.8  1695.7   141.1 1691.88   170.4 1682.67   180.2 1680.61   196.5 1680.54
   199.7 1680.22     203 1679.18   209.5 1677.52   214.4 1677.36   219.3 1677.69
   222.5 1679.68   225.8 1681.02     229 1681.28   264.8 1681.13   281.1 1682.95
   333.2 1683.84   346.2 1684.78   359.3 1687.44   372.3 1690.96   385.3 1695.21
   398.3 1698.55   460.2 1703.59  503.461708.973   512.3 1710.23   515.5 1711.68
#Mann= 4 ,-1 , 0
       0     .12       0     203    .045       0   222.5     .12       0
  503.46    .016       0
Bank Sta=203,222.5
XS Rating Curve= 0 ,0
Exp/Cntr=0.3,0.1

Type RM Length L Ch R = 1 ,7203.7  ,207.6,207.5,207.5
XS GIS Cut Line= 3
     2020707.361      178738.566     2020827.845      178782.107
      2021083.58      178978.993
#Sta/Elev= 30
       0 1795.67     6.4 1792.17    19.2 1783.81    57.6 1753.97    67.3  1745.2
    70.5 1743.05    80.1 1738.28    99.3 1722.26   128.1 1701.76   147.7 1689.19
   157.4 1683.63     164 1681.56   180.3 1679.76     195 1677.18   199.8 1676.61
   209.6 1676.71  210.97 1677.22   216.1 1679.58   219.4 1680.23   232.4 1679.97
     265 1680.81   281.3 1681.76   300.9  1683.7     327 1689.03  364.631697.926
   375.9 1702.54   395.4 1703.11  405.291705.434   424.8 1710.75   450.9 1719.99
#Mann= 5 ,-1 , 0
       0     .12       0     195    .045       0  210.97     .12       0
  364.63    .016       0  405.29     .12       0
Bank Sta=195,210.97
XS Rating Curve= 0 ,0
Exp/Cntr=0.3,0.1

Type RM Length L Ch R = 1 ,6996.2  ,236.5,235.3,232.3
XS GIS Cut Line= 2
     2020629.636      178888.671     2020939.599      179129.259
#Sta/Elev= 30
       0 1767.02    26.2 1750.54    32.7 1746.02    68.7  1717.9    94.8 1696.38
   104.6 1689.15   111.2 1683.63   114.4 1681.81     121 1680.26   134.1 1679.34
   150.4 1678.68   166.8 1679.32     170 1679.08   173.3 1678.13   176.6 1676.73
   179.8 1676.06   186.4  1676.5   189.6 1677.45   202.7 1680.14   232.2 1682.59
   264.8 1687.14   317.2 1696.86  330.35 1697.21   346.6 1699.81   359.7    1700
     363 1700.73   366.2 1702.68   369.5 1703.99   385.8 1705.43   392.4 1706.54
#Mann= 4 ,-1 , 0
       0     .12       0   173.3    .045       0   189.6     .12       0
  330.35    .016       0
Bank Sta=173.3,189.6
XS Rating Curve= 0 ,0
Exp/Cntr=0.3,0.1

Type RM Length L Ch R = 1 ,6760.8  ,138.6,136,134.5
XS GIS Cut Line= 3
     2020524.201      179077.108      2020535.92       179120.51
      2020817.17      179304.972
#Sta/Elev= 30
       0 1703.27     6.4 1701.09    16.1 1699.28      45 1691.32    54.8 1689.31
    90.7  1684.9   103.7  1682.2   110.3 1681.28   120.1 1678.29   133.1 1677.66
   137.7 1676.56   146.2 1675.88   152.7 1676.51   159.2  1678.3  162.341678.576
     218 1679.29   227.8  1679.9     254 1682.07   270.3 1684.04   276.8  1685.2
  288.85 1688.33   306.2 1694.23   319.3 1695.61   325.8 1699.03   342.1 1699.74
   351.9 1705.77  356.021707.678   361.7 1709.63     365 1710.05   381.3 1710.42
#Mann= 6 ,-1 , 0
       0     .12       0   137.7    .045       0   152.7     .12       0
  162.34     .06       0  288.85    .016       0  356.02     .12       0
Bank Sta=137.7,152.7
XS Rating Curve= 0 ,0
Exp/Cntr=0.3,0.1

Type RM Length L Ch R = 1 ,6624.8  ,58.1,58.8,59.2
XS GIS Cut Line= 3
     2020476.892      179167.385     2020515.086      179269.816
     2020788.524      179410.441
#Sta/Elev= 30
       0 1696.82    16.1 1694.94    51.4 1689.45    61.1 1685.76      74 1683.44
    83.6 1682.62   102.9 1682.68   119.1 1681.72   122.4 1680.83     129 1677.48
   134.4 1676.49   145.3 1675.86  150.58 1676.51   158.4 1678.25  191.441677.341
   204.2 1676.51     214 1676.78   233.6 1678.51  263.661682.557   279.4    1684
     299  1690.6   305.6 1693.34   312.1 1697.33  316.281700.596   318.7 1701.85
   321.9 1702.32   331.8 1702.78  349.061710.352   390.6 1723.39   416.8 1730.12
#Mann= 7 ,-1 , 0
       0     .12       0   134.4    .045       0  150.58     .12       0
  191.44     .06       0  263.66     .12       0  316.28    .016       0
  349.06     .12       0
#XS Ineff= 2 , 0
          123.58 1682.66
Permanent Ineff=
       F       F
Bank Sta=134.4,150.58
XS Rating Curve= 0 ,0
Exp/Cntr=0.3,0.1

Type RM Length L Ch R = 1 ,6566.1  ,95.2,112,128.1
XS GIS Cut Line= 2
     2020364.045      179255.927     2020765.086      179462.524
#Sta/Elev= 30
       0 1700.83   18.91 1694.42    26.2 1691.63    39.2 1690.81    55.6 1686.13
    65.4 1684.06  122.431681.615   163.4 1679.54     170  1678.3   176.5 1675.79
   186.3 1674.98   193.3 1676.13   202.7 1677.53   225.6 1676.41   261.5 1676.94
   274.6 1678.49  280.741680.143   300.8 1687.06  307.971688.435  312.121689.011
   317.1 1690.86     340 1702.36   356.3 1703.13   362.9 1706.99  370.091708.785
   382.5 1712.08   408.6 1720.62   421.7 1723.39   441.3 1725.83   451.1 1729.57
#Mann= 9 ,-1 , 0
       0     .12       0   18.91     .06       0  122.43     .12       0
   176.5    .045       0   193.3     .12       0  280.74     .06       0
  307.97     .12       0  312.12    .016       0  370.09     .12       0
Bank Sta=176.5,193.3
XS Rating Curve= 0 ,0
Exp/Cntr=0.3,0.1

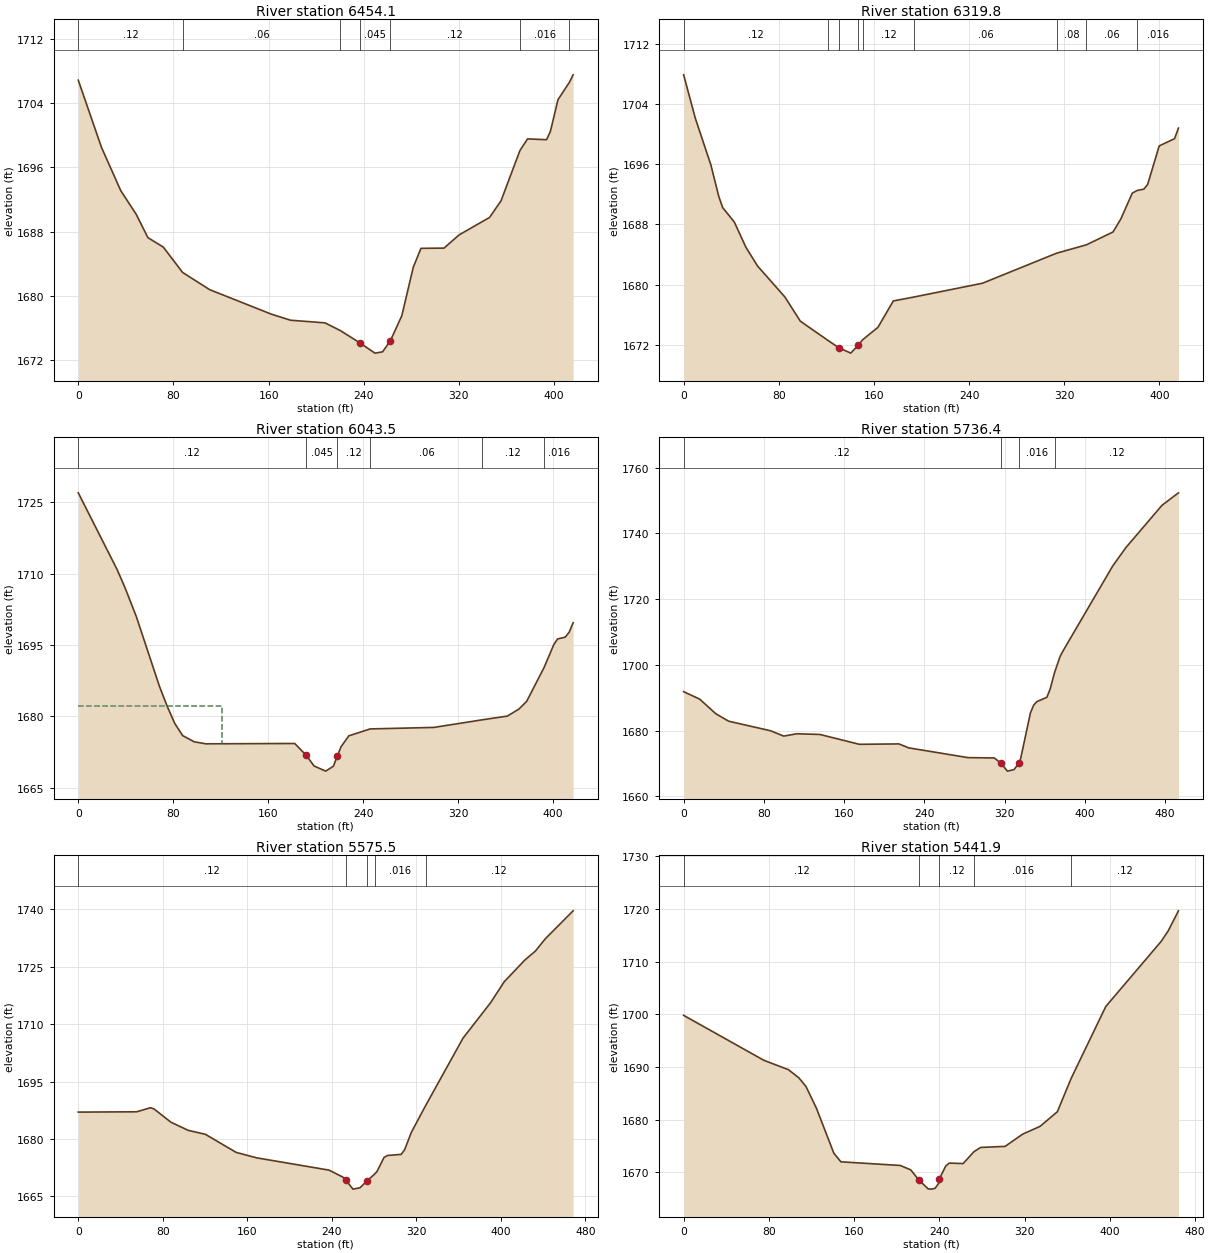
Type RM Length L Ch R = 1 ,6454.1  ,130.8,134.3,138
XS GIS Cut Line= 4
     2020334.893      179270.265     2020446.872      179336.237
      2020510.24      179502.035     2020601.386      179561.063
#Sta/Elev= 30
       0 1706.85    19.5 1698.49    35.7  1693.1    48.7 1690.15    58.5 1687.25
    71.5 1686.06    87.7 1682.91   110.5 1680.76   162.2 1677.72   178.4 1676.96
   207.4 1676.63   220.3 1675.67   236.5 1674.16   249.4 1672.86   255.8 1673.02
   262.3 1674.37     272 1677.52   281.6 1683.54   288.1 1685.91   307.5 1685.94
   320.2 1687.59   345.8 1689.76   355.4 1691.83   371.3 1698.09   377.7 1699.54
   393.7 1699.44   396.9 1700.47   403.3 1704.43   412.9 1706.59     416 1707.52
#Mann= 7 ,-1 , 0
       0     .12       0    87.7     .06       0   220.3     .12       0
   236.5    .045       0   262.3     .12       0   371.3    .016       0
   412.9     .12       0
Bank Sta=236.5,262.3
XS Rating Curve= 0 ,0
Exp/Cntr=0.3,0.1

Type RM Length L Ch R = 1 ,6319.8  ,297.4,276.3,255.4
XS GIS Cut Line= 4
     2020283.316      179350.545     2020343.211      179384.399
     2020378.368      179566.691     2020518.993      179646.118
#Sta/Elev= 30
       0 1707.89     9.8 1702.13    22.9 1695.91    29.5 1691.75    32.8 1690.24
    42.6 1688.32    52.4 1684.95    62.2 1682.46    85.1 1678.36    98.1 1675.14
  121.151672.602   130.7 1671.58   140.5 1670.89     147 1671.99   150.7  1672.7
   163.3 1674.31   176.3 1677.83  193.791678.354   251.2 1680.18  313.671684.184
  338.571685.285     361    1687   367.5 1688.71   377.2 1692.17  381.521692.527
   386.9 1692.69   390.1 1693.32   399.8 1698.44   412.7  1699.4     416 1700.81
#Mann= 9 ,-1 , 0
       0     .12       0  121.15     .06       0   130.7    .045       0
     147     .06       0   150.7     .12       0  193.79     .06       0
  313.67     .08       0  338.57     .06       0  381.52    .016       0
Bank Sta=130.7,147
XS Rating Curve= 0 ,0
Exp/Cntr=0.3,0.1

Type RM Length L Ch R = 1 ,6043.5  ,305,307.1,306.4
XS GIS Cut Line= 2
     2020063.698      179578.844     2020438.698      179761.135
#Sta/Elev= 30
       0 1727.02    32.6 1710.95    39.1 1707.25    48.9 1701.02    68.4 1686.34
    74.9 1682.16    81.4 1678.49      88 1675.97    97.7 1674.68   107.5 1674.25
   182.4 1674.32   192.1 1671.84   198.7 1669.59   208.5 1668.51     215 1669.54
   218.2 1671.63   221.5 1673.66     228 1675.93     2461677.383   299.7  1677.7
  340.641679.307   361.6 1680.08   371.4 1681.57   377.9 1683.19  392.571690.316
   400.7 1695.09   403.9  1696.3   410.4 1696.68   413.7 1697.72     417 1699.71
#Mann= 6 ,-1 , 0
       0     .12       0   192.1    .045       0   218.2     .12       0
     246     .06       0  340.64     .12       0  392.57    .016       0
#XS Ineff= 2 , 0
          120.74  1682.2
Permanent Ineff=
       F       F
Bank Sta=192.1,218.2
XS Rating Curve= 0 ,0
Exp/Cntr=0.3,0.1

Type RM Length L Ch R = 1 ,5736.4  ,161.5,160.9,159.3
XS GIS Cut Line= 3
     2019997.291      179844.469      2020080.65      179844.652
     2020456.059      180009.399
#Sta/Elev= 30
       0 1691.84      16 1689.57    32.1 1685.12    44.9 1682.85    86.6 1679.95
    99.8 1678.32   112.9 1679.03   135.8 1678.82   175.2 1675.82   214.6 1675.94
   224.4 1674.74   283.4 1671.77   309.7 1671.67   316.2  1670.1   322.8 1667.66
   329.3  1668.1  334.07 1669.99   335.9 1671.37   345.7 1685.34     349 1687.79
   352.3 1688.83   362.1 1690.12   365.4 1692.64  369.861697.736   375.3 1702.58
   378.5 1704.38   427.7 1730.06   440.8 1735.65   476.9 1748.56   493.3 1752.35
#Mann= 4 ,-1 , 0
       0     .12       0   316.2    .045       0  334.07    .016       0
  369.86     .12       0
Bank Sta=316.2,334.07
XS Rating Curve= 0 ,0
Exp/Cntr=0.3,0.1

Type RM Length L Ch R = 1 ,5575.5  ,134.8,133.6,131.9
XS GIS Cut Line= 3
     2019961.701      179974.243       2020232.1      180077.108
      2020410.92      180070.163
#Sta/Elev= 30
       0 1687.02    55.3  1687.1    68.3 1688.16    71.5 1687.88    87.8 1684.36
     104 1682.26   120.3 1681.22   149.5 1676.49     169 1675.07   237.3 1671.87
   250.3 1670.07   253.4 1669.17     260 1666.91   266.6 1667.26     273 1668.99
  280.411670.818   282.8 1671.55   289.3 1675.15   292.6 1675.69   305.6 1675.98
   308.8 1677.16   315.3 1681.78  328.641688.669   364.1 1706.32   390.2 1715.58
   403.2 1721.08   422.7 1726.74   432.5 1729.03   442.2 1732.33   468.3 1739.57
#Mann= 5 ,-1 , 0
       0     .12       0   253.4    .045       0     273     .12       0
  280.41    .016       0  328.64     .12       0
Bank Sta=253.4,273
XS Rating Curve= 0 ,0
Exp/Cntr=0.3,0.1

Type RM Length L Ch R = 1 ,5441.9  ,158,140,121.2
XS GIS Cut Line= 3
     2019925.243      180103.149     2020242.951      180217.733
     2020366.649      180190.389
#Sta/Elev= 30
       0 1699.79    75.4 1691.25    98.4 1689.48   108.2 1687.92   114.8  1686.3
   124.6 1682.18     141 1673.62   147.6    1672   203.3 1671.31   213.1 1670.48
     221  1668.5   229.5 1666.87   232.8 1666.82     236 1666.98   239.4 1667.93
  240.06 1668.79   245.9 1671.18   249.2 1671.76   262.3 1671.67  272.491673.928
   278.7 1674.73   301.7 1674.93   318.1 1677.24   334.5 1678.73   350.7 1681.49
  363.641687.808   396.2 1701.47   448.2 1713.83   454.7 1715.79   464.4 1719.62
#Mann= 5 ,-1 , 0
       0     .12       0     221    .045       0  240.06     .12       0
  272.49    .016       0  363.64     .12       0
Bank Sta=221,240.06
XS Rating Curve= 0 ,0
Exp/Cntr=0.3,0.1