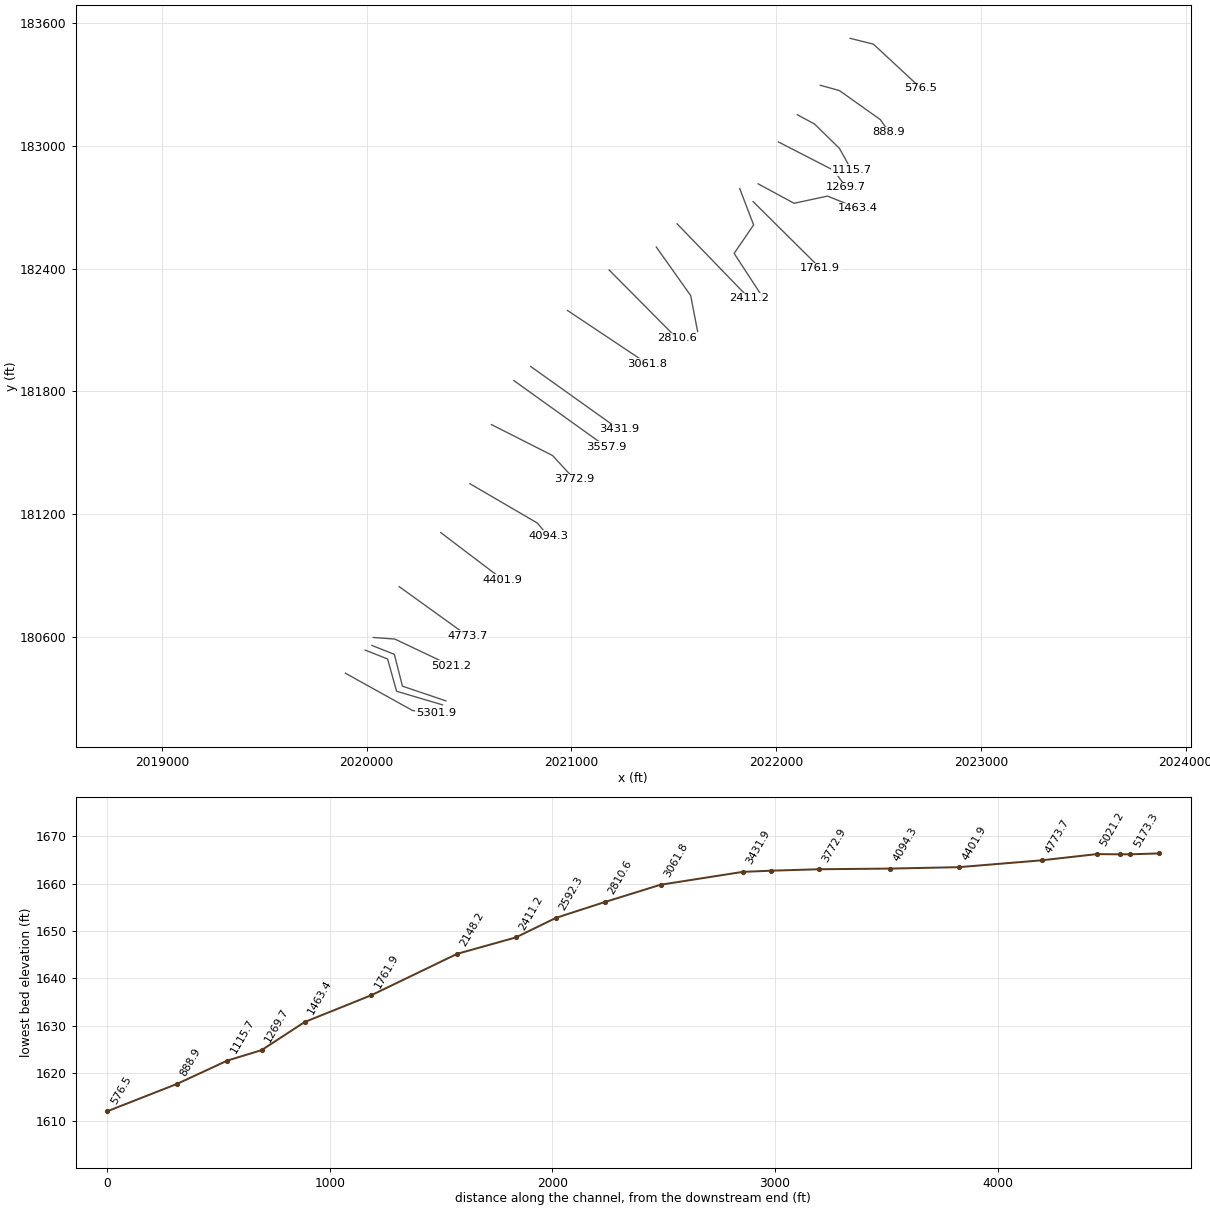
HEC-RAS study STNKLKCK.prj: STNKLKCK

--- STNKLKCK.g01 (geometry) --- (continued)

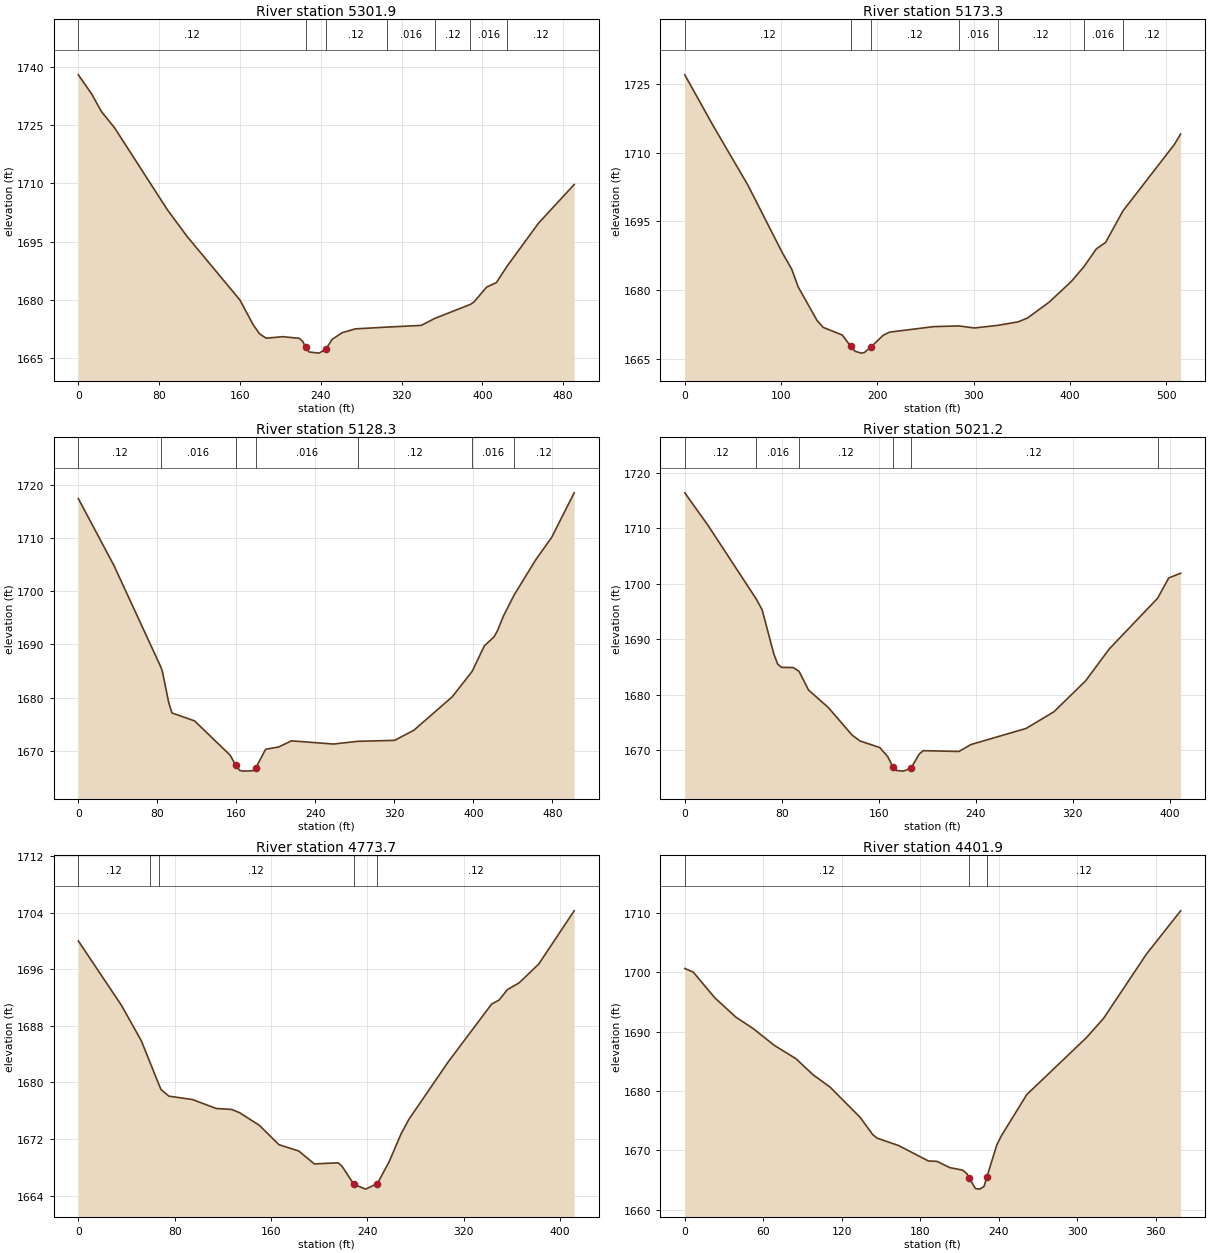
Type RM Length L Ch R = 1 ,5301.9  ,148.3,128.6,73.5
XS GIS Cut Line= 3
     2019896.597       180424.33     2020224.722      180242.038
     2020339.305      180228.149
#Sta/Elev= 30
       0 1737.95    13.1 1733.08    22.8 1728.53    35.9 1724.31    88.1 1703.26
   107.7 1696.37   159.9 1680.06     173 1673.71   179.5  1671.3     186 1670.21
   202.4  1670.6   218.7 1670.18     222 1669.42   225.2 1667.84   228.5 1666.66
   238.3 1666.37   244.9 1667.38   251.3 1669.92   261.1 1671.62   274.2 1672.61
  305.051673.056   339.5 1673.51  352.871675.304  387.891678.882   391.4 1679.47
   404.2 1683.36   413.8 1684.51   424.81688.879   455.5 1699.79   490.8 1709.73
#Mann= 7 ,-1 , 0
       0     .12       0   225.2    .045       0   244.9     .12       0
  305.05    .016       0  352.87     .12       0  387.89    .016       0
   424.8     .12       0
Bank Sta=225.2,244.9
XS Rating Curve= 0 ,0
Exp/Cntr=0.3,0.1

Type RM Length L Ch R = 1 ,5173.3  ,47.3,45,78.8
XS GIS Cut Line= 4
     2019993.385      180537.177      2020102.76      180493.774
     2020146.597      180336.222     2020370.555      180269.816
#Sta/Elev= 30
       0 1727.02    29.4 1715.91    65.4 1702.95   101.3 1688.11   111.1  1684.5
   117.7 1680.66   137.3 1673.33   143.8  1671.8   163.5 1670.14   172.3 1667.67
   176.6  1666.6   183.1 1666.18   186.4 1666.31   192.9 1667.45     206 1670.08
   212.5 1670.77   258.3 1671.97  284.45 1672.13   300.7 1671.68     325 1672.25
   346.1 1673.02   355.8 1673.85   378.5 1677.36   401.2 1681.82  414.471685.092
   427.2 1688.95   436.9 1690.38  454.911697.268   508.3  1711.8   514.8 1714.09
#Mann= 7 ,-1 , 0
       0     .12       0   172.3    .045       0   192.9     .12       0
  284.45    .016       0     325     .12       0  414.47    .016       0
  454.91     .12       0
Bank Sta=172.3,192.9
XS Rating Curve= 0 ,0
Exp/Cntr=0.3,0.1

Type RM Length L Ch R = 1 ,5128.3  ,83.5,107.1,129.3
XS GIS Cut Line= 4
     2020026.371      180559.747     2020135.746      180516.344
     2020175.243      180360.962     2020387.482      180289.347
#Sta/Elev= 30
       0 1717.39      36 1704.84   83.551685.741      85 1684.99    91.5 1679.09
    94.8 1677.11   117.7 1675.62   153.7 1669.18   159.2 1667.34   163.5  1666.3
   166.8 1666.18   176.6 1666.25   179.8 1666.82   189.6 1670.28   202.7 1670.71
   215.8 1671.87   258.4 1671.27  283.361671.786   320.2 1671.96   339.7 1673.86
   378.6 1680.15  398.731684.932   411.1 1689.73   420.8 1691.39   424.1 1692.46
   430.6  1695.4  441.41 1699.33     463 1705.86   479.3 1710.12     502 1718.47
#Mann= 7 ,-1 , 0
       0     .12       0   83.55    .016       0   159.2    .045       0
   179.8    .016       0  283.36     .12       0  398.73    .016       0
  441.41     .12       0
Bank Sta=159.2,179.8
XS Rating Curve= 0 ,0
Exp/Cntr=0.3,0.1

Type RM Length L Ch R = 1 ,5021.2  ,249.5,247.5,241.9
XS GIS Cut Line= 3
     2020033.316      180598.809      2020138.35      180590.997
     2020412.656      180460.788
#Sta/Elev= 30
       0 1716.38    19.2  1710.5   58.931697.247    63.8  1695.3    73.4 1687.37
    76.6 1685.52    79.8 1684.92    89.4 1684.89   94.271684.197   102.1 1680.83
   118.4 1677.68     138 1672.72   144.5 1671.66   160.8 1670.47   167.4 1668.84
   171.6 1666.99   173.9 1666.36   180.4 1666.22   186.6 1666.77   193.5 1669.33
   196.7 1669.91   226.1 1669.76   235.9    1671   281.6 1673.92   304.5 1676.92
   330.6 1682.49   350.2 1688.26  390.01 1697.38   399.2 1701.04     409 1701.89
#Mann= 6 ,-1 , 0
       0     .12       0   58.93    .016       0   94.27     .12       0
   171.6    .045       0   186.6     .12       0  390.01    .016       0
Bank Sta=171.6,186.6
XS Rating Curve= 0 ,0
Exp/Cntr=0.3,0.1

Type RM Length L Ch R = 1 ,4773.7  ,369.8,371.8,368.7
XS GIS Cut Line= 2
     2020159.184      180847.073     2020493.385      180606.622
#Sta/Elev= 30
       0 1699.99    35.9 1690.86    52.3 1685.88   59.161682.973   66.721679.764
    68.6    1679    75.2 1678.05    94.8 1677.57   114.4 1676.31   127.4 1676.17
     134  1675.7   150.3 1673.93   166.6 1671.19     183  1670.3     196 1668.47
   215.7 1668.63   218.9 1668.16   228.7 1665.61   238.5 1664.91   248.3 1665.69
   258.1 1668.79   267.9 1672.69   274.5 1674.78   307.2 1682.91   343.1 1691.05
   349.6 1691.66   356.2  1693.1     366 1694.06   382.3 1696.72   411.7 1704.24
#Mann= 5 ,-1 , 0
       0     .12       0   59.16     .06       0   66.72     .12       0
   228.7    .045       0   248.3     .12       0
Bank Sta=228.7,248.3
XS Rating Curve= 0 ,0
Exp/Cntr=0.3,0.1

Type RM Length L Ch R = 1 ,4401.9  ,304.3,307.6,309.6
XS GIS Cut Line= 2
     2020362.309      181110.962     2020664.392      180881.795
#Sta/Elev= 30
       0 1700.61     6.5    1700    22.9 1695.69    39.2  1692.4    52.3  1690.5
    68.6 1687.65      85 1685.43    98.1 1682.72   111.1 1680.65     134 1675.58
   143.8 1672.63   147.1 1672.05   163.4 1670.82   186.3 1668.21   192.8 1668.15
   202.7 1667.09   212.5 1666.67   215.7 1666.08  217.32  1665.4   222.3 1663.57
   225.5 1663.47   228.8 1663.91  230.91 1665.43   238.6  1670.9   241.9 1672.37
   261.5 1679.38   307.3    1689   320.3 1692.23     353 1703.02   379.2 1710.32
#Mann= 3 ,-1 , 0
       0     .12       0  217.32    .045       0  230.91     .12       0
Bank Sta=217.32,230.91
XS Rating Curve= 0 ,0
Exp/Cntr=0.3,0.1

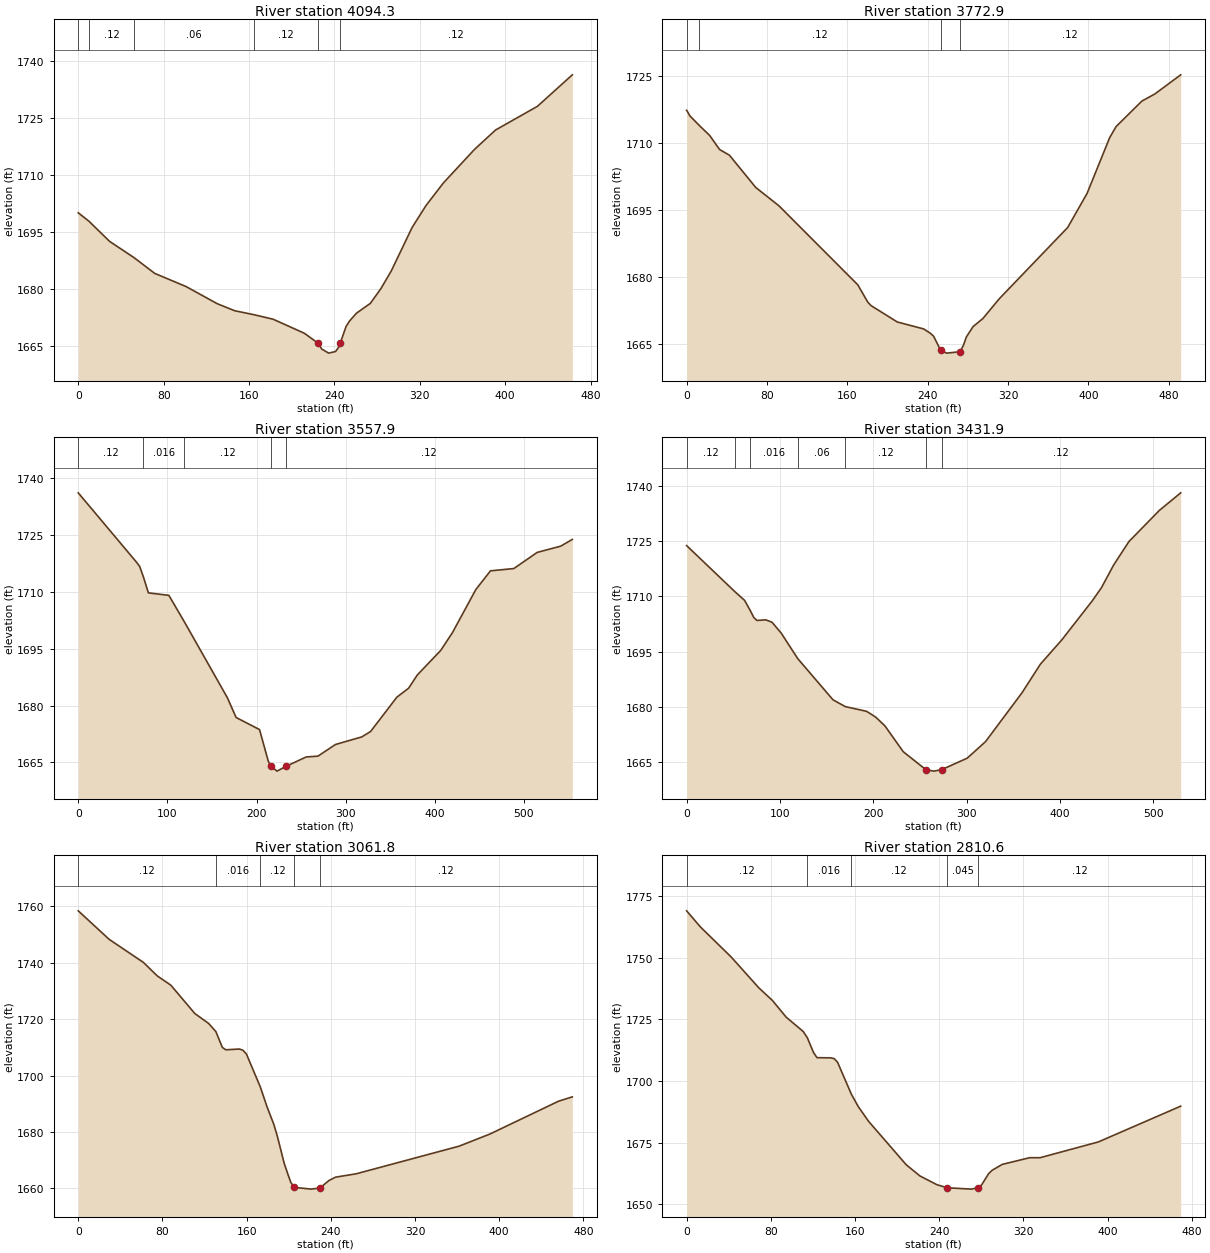
Type RM Length L Ch R = 1 ,4094.3  ,319.8,321.4,322.4
XS GIS Cut Line= 3
      2020504.91      181349.512     2020834.239      181157.482
     2020886.374      181094.634
#Sta/Elev= 30
       0 1700.06    9.931697.864    29.3 1692.56   52.351688.251    71.7 1684.12
     101 1680.67   130.3 1676.15   146.6 1674.31  164.241673.294   182.5 1672.09
   211.8  1668.4   224.8 1665.76   228.1 1664.25   234.6 1663.17   241.1 1663.59
   244.4 1664.89   245.6 1665.88   250.9 1670.17   254.2 1671.62   260.7 1673.67
   273.7 1676.25   283.5  1680.1   293.2 1684.72   312.8 1696.19   325.8 1701.95
   342.1 1707.89   371.4 1716.75     391 1721.81   430.2 1728.03   462.9 1736.31
#Mann= 6 ,-1 , 0
       0     .06       0    9.93     .12       0   52.35     .06       0
  164.24     .12       0   224.8    .045       0   245.6     .12       0
Bank Sta=224.8,245.6
XS Rating Curve= 0 ,0
Exp/Cntr=0.3,0.1

Type RM Length L Ch R = 1 ,3772.9  ,218,215,211.6
XS GIS Cut Line= 3
     2020610.139      181638.306     2020908.316      181487.264
     2021015.086      181371.379
#Sta/Elev= 30
       0  1717.4     3.3 1716.14   12.541714.017    22.9 1711.77    32.8 1708.62
    42.6 1707.34    68.8 1700.12    91.8 1696.03   170.4 1678.32   180.2 1674.48
   183.5 1673.68   209.7    1670   235.9 1668.45   242.5  1667.5   245.8 1666.83
   252.9 1663.64   258.9 1663.03     272 1663.34   275.3 1664.66   278.5 1666.67
   285.1 1668.96   294.9 1670.78   311.3 1675.23   379.3 1691.16   398.6 1698.79
   421.1 1711.28   427.5 1713.76   453.2 1719.47   466.1 1721.06   491.8 1725.34
#Mann= 4 ,-1 , 0
       0    .016       0   12.54     .12       0   252.9    .045       0
     272     .12       0
Bank Sta=252.9,272
XS Rating Curve= 0 ,0
Exp/Cntr=0.3,0.1

Type RM Length L Ch R = 1 ,3557.9  ,125,126,126.6
XS GIS Cut Line= 2
     2020719.514      181853.149     2021170.034      181530.233
#Sta/Elev= 30
       0 1736.16    65.6 1717.79    68.9 1716.75   73.161713.947    78.7 1709.76
   101.7  1709.1  119.041702.124   167.3  1682.1   177.1 1676.88   203.4 1673.68
   213.2 1665.36   215.8  1664.1     223 1662.72   232.9 1663.96   255.8 1666.46
     269 1666.68   288.6 1669.75   318.2 1671.76     328 1673.18   357.5 1682.24
   370.6 1684.59   380.5 1688.12   406.7 1694.58   419.8 1699.26   446.1 1710.65
   462.5 1715.57   488.7 1716.18   514.9 1720.44   541.2 1722.08   554.3 1723.86
#Mann= 5 ,-1 , 0
       0     .12       0   73.16    .016       0  119.04     .12       0
   215.8    .045       0   232.9     .12       0
Bank Sta=215.8,232.9
XS Rating Curve= 0 ,0
Exp/Cntr=0.3,0.1

Type RM Length L Ch R = 1 ,3431.9  ,369.7,370.1,369
XS GIS Cut Line= 2
     2020801.545       181922.16     2021232.534      181614.868
#Sta/Elev= 30
       0 1723.83   51.421711.361    62.1 1708.93   68.16 1706.16    71.9  1704.3
    75.2 1703.48      85 1703.62    91.5 1702.98   101.3 1700.03  119.041693.089
   156.8 1681.88  169.921680.039   192.8 1678.75   202.6 1677.16   212.4  1674.8
     232 1667.78  256.27 1662.88   264.7 1662.48   273.2 1662.88   300.6 1666.01
   320.2  1670.5   359.4 1683.84     379 1691.58   401.9 1698.18   434.6 1708.82
   444.4 1712.39   457.4 1718.53   473.8 1724.93   506.4  1733.4   529.3 1738.19
#Mann= 7 ,-1 , 0
       0     .12       0   51.42     .06       0   68.16    .016       0
  119.04     .06       0  169.92     .12       0  256.27    .045       0
   273.2     .12       0
Bank Sta=256.27,273.2
XS Rating Curve= 0 ,0
Exp/Cntr=0.3,0.1

Type RM Length L Ch R = 1 ,3061.8  ,255.5,251.2,246.6
XS GIS Cut Line= 2
     2020981.232      182195.597     2021371.857      181935.181
#Sta/Elev= 30
       0 1758.43    29.3 1748.34    61.9 1740.15      75 1735.39      88 1732.06
   110.8 1722.02   123.9  1718.5  130.791715.616   136.9 1710.02   140.2 1709.16
   153.2 1709.43   156.5    1709   159.8 1707.68  173.071695.954   179.3 1689.06
   185.8 1682.78   189.1 1678.67   195.6 1669.06   198.9 1665.39   202.1 1662.06
   205.4 1660.37   221.7 1659.76  229.91 1660.22     238 1662.75   244.5    1664
   264.1 1665.19   361.9 1674.99   391.2 1679.29   456.4 1690.93   469.5 1692.47
#Mann= 5 ,-1 , 0
       0     .12       0  130.79    .016       0  173.07     .12       0
   205.4    .045       0  229.91     .12       0
Bank Sta=205.4,229.91
XS Rating Curve= 0 ,0
Exp/Cntr=0.3,0.1

Type RM Length L Ch R = 1 ,2810.6  ,221.5,218.3,214.4
XS GIS Cut Line= 2
     2021184.345      182393.435     2021515.099      182060.259
#Sta/Elev= 30
       0 1769.07      13 1762.56    42.4  1750.3    68.5 1737.85    81.5 1732.69
    94.6  1725.9   110.8 1720.08   114.71717.554   120.6 1711.53   123.9 1709.46
   136.9 1709.39   140.2 1709.07   143.4 1707.62  156.491694.679     163 1689.66
   172.8 1683.67   208.6 1666.02   221.7 1661.45     238 1657.86   247.8 1656.65
   270.6  1656.1   277.1 1656.71   280.4 1657.88   286.9 1662.33   290.2 1663.72
   299.9 1666.14     326 1668.86   335.8 1668.85   391.2 1675.25   469.5 1689.78
#Mann= 5 ,-1 , 0
       0     .12       0   114.7    .016       0  156.49     .12       0
   247.8    .045       0   277.1     .12       0
Bank Sta=247.8,277.1
XS Rating Curve= 0 ,0
Exp/Cntr=0.3,0.1

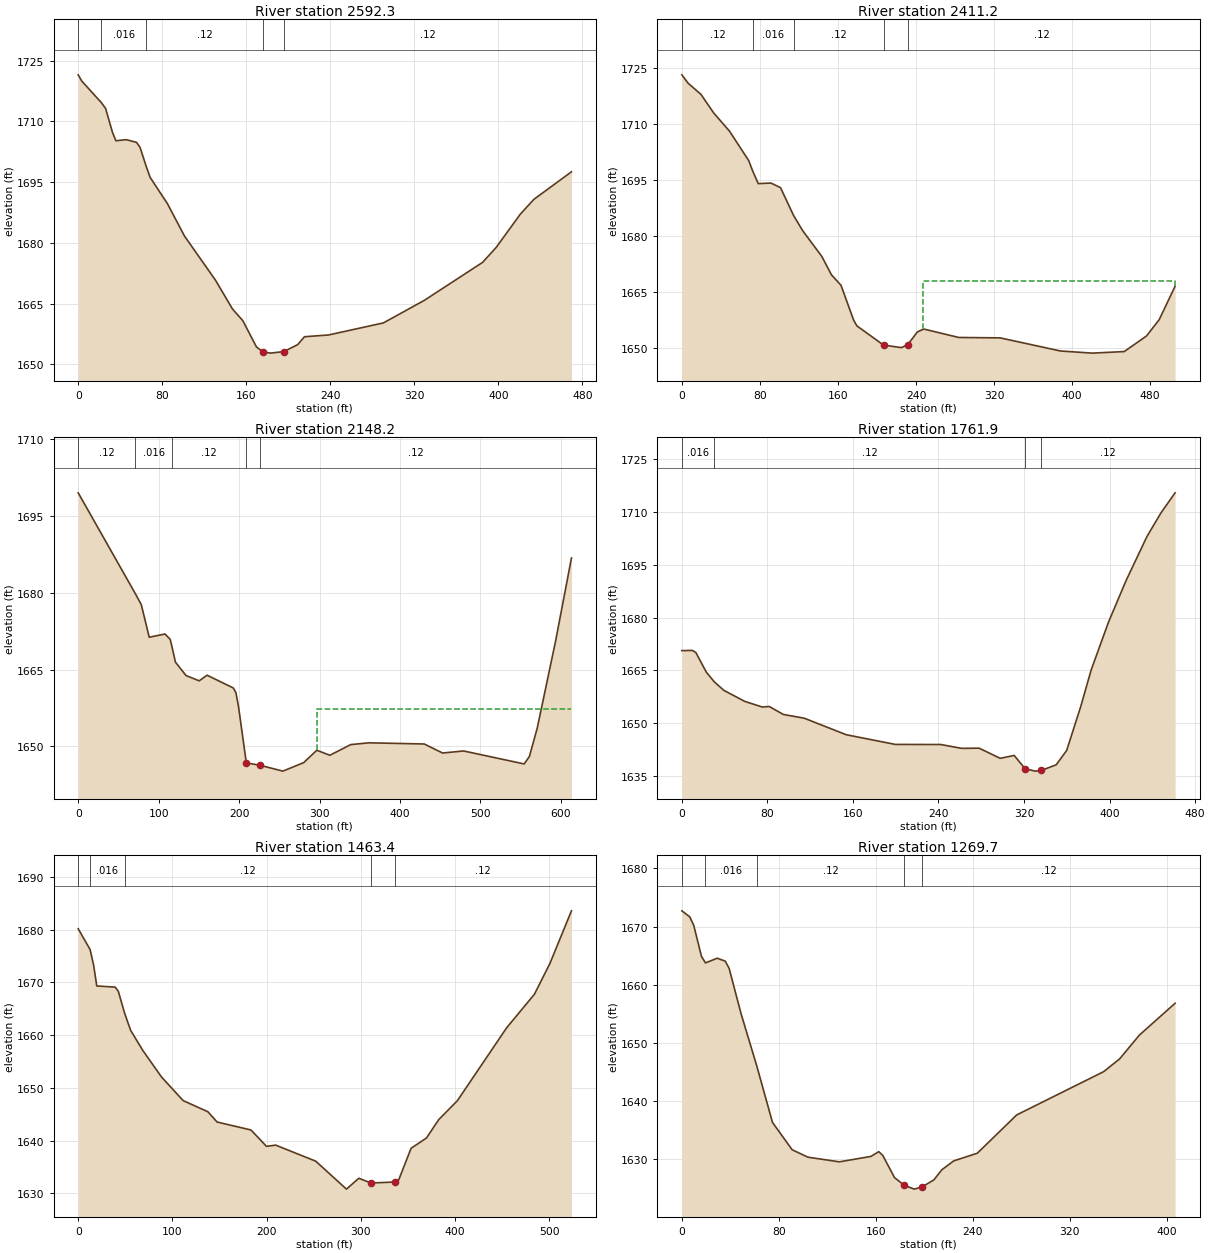
Type RM Length L Ch R = 1 ,2592.3  ,177.6,181.1,184.4
XS GIS Cut Line= 3
     2021414.826      182505.493     2021582.795      182268.514
     2021616.649      182092.733
#Sta/Elev= 30
       0 1721.51     3.3    1720   22.161714.604    26.1  1713.2    32.6 1707.32
    35.9 1705.22    45.7  1705.5    55.5 1704.83    58.8 1703.63   64.821698.841
    68.5 1696.17    84.9 1689.71   101.2 1681.68   130.6 1670.82   146.9 1663.66
   156.7 1660.79   169.7  1654.3   175.9  1653.1   182.8 1652.78   195.8 1653.16
   208.9 1654.88   215.4 1656.83   238.2 1657.26   290.5 1660.24   329.5 1665.82
   384.9 1675.19   397.9  1678.9   420.7 1687.06   433.7 1690.75   469.5 1697.56
#Mann= 5 ,-1 , 0
       0     .12       0   22.16    .016       0   64.82     .12       0
   175.9    .045       0   195.8     .12       0
Bank Sta=175.9,195.8
XS Rating Curve= 0 ,0
Exp/Cntr=0.3,0.1

Type RM Length L Ch R = 1 ,2411.2  ,293.9,263,230.7
XS GIS Cut Line= 2
     2021516.389      182618.774     2021867.951      182255.493
#Sta/Elev= 30
       0 1723.11     6.5 1720.85    19.6 1717.88    32.6 1712.92    48.9 1708.02
    68.5 1700.17   72.871697.224    78.3    1694    91.3 1694.15   101.1 1692.93
  114.441685.506   123.9 1681.38   143.5  1674.5   153.3  1669.6   163.1  1666.8
   176.1 1657.45   179.4 1655.93   206.7 1650.79     225 1650.11   231.6 1650.93
   241.4 1654.32   247.9 1655.09   283.8 1652.83   326.2 1652.72   388.1 1649.21
   420.7 1648.64   453.4 1649.06   476.2 1653.23   489.2 1657.59   505.5 1666.54
#Mann= 5 ,-1 , 0
       0     .12       0   72.87    .016       0  114.44     .12       0
   206.7    .045       0   231.6     .12       0
#XS Ineff= 2 , 0
                          247.16         1667.86
Permanent Ineff=
       F       F
Bank Sta=206.7,231.6
XS Rating Curve= 0 ,0
Exp/Cntr=0.3,0.1

Type RM Length L Ch R = 1 ,2148.2  ,353.1,386.3,418.1
XS GIS Cut Line= 4
     2021822.378      182790.649     2021890.086      182613.566
     2021795.034      182474.243     2021934.357      182260.701
#Sta/Elev= 30
       0 1699.44   70.861679.831    78.4 1677.66    88.3 1671.29   107.9 1671.92
   114.4 1670.87  116.97 1669.18   120.9 1666.43     134 1663.83   150.4 1662.79
   160.2 1663.89   192.8  1661.4   196.1 1660.47   199.3 1657.77     209  1646.8
   226.6 1646.31   254.4 1645.19   280.4 1646.85   296.6 1649.26   312.8 1648.28
   338.8 1650.36   361.5 1650.71   430.2 1650.48     453 1648.72   479.2 1649.12
   554.4 1646.59   560.9 1648.04   570.7  1653.6   593.6 1670.64   613.2 1686.74
#Mann= 5 ,-1 , 0
       0     .12       0   70.86    .016       0  116.97     .12       0
     209    .045       0   226.6     .12       0
#XS Ineff= 2 , 0
                          296.31         1657.27
Permanent Ineff=
       F       F
Bank Sta=209,226.6
XS Rating Curve= 0 ,0
Exp/Cntr=0.3,0.1

Type RM Length L Ch R = 1 ,1761.9  ,274.9,298.5,320
XS GIS Cut Line= 2
     2021887.803      182727.181     2022215.287      182402.294
#Sta/Elev= 30
       0 1670.63     9.8  1670.7    13.1  1670.1    22.9 1664.51   30.351661.786
    39.3 1659.36    58.9 1656.23    75.2 1654.64    81.8 1654.78    94.9 1652.53
   114.5 1651.46   153.8 1646.77   199.6 1644.03   242.1    1644   261.7 1642.91
   278.1 1642.96   297.7 1640.08   310.8  1640.9     321 1637.15   330.4 1636.45
     336 1636.63   350.1 1638.24   359.9 1642.32     373 1654.72   382.8 1665.15
   399.1 1678.78   415.5 1690.54   435.1 1703.08   448.2 1709.76   461.3  1715.4
#Mann= 4 ,-1 , 0
       0    .016       0   30.35     .12       0     321    .045       0
     336     .12       0
Bank Sta=321,336
XS Rating Curve= 0 ,0
Exp/Cntr=0.3,0.1

Type RM Length L Ch R = 1 ,1463.4  ,209,193.7,177.7
XS GIS Cut Line= 4
     2021912.222      182814.087     2022088.003      182719.035
     2022250.764      182754.191     2022396.597      182695.597
#Sta/Elev= 30
       0 1680.18   12.631676.228    16.4 1673.25    19.7 1669.33    39.3 1669.11
    42.6  1668.3    49.41664.092    55.7  1660.9    68.8 1657.05    88.4 1652.08
   111.4  1647.6   137.6 1645.49   147.4 1643.54   183.4 1642.03   199.8 1638.93
   209.6 1639.16   252.1 1636.12   284.7 1630.82   297.8 1632.88   310.8 1631.98
   336.2 1632.17   340.2 1632.59   353.3 1638.56   369.6 1640.51   382.7 1644.01
   402.4 1647.58   454.8 1661.42   484.2 1667.76   500.6 1673.58   523.5 1683.57
#Mann= 5 ,-1 , 0
       0     .12       0   12.63    .016       0    49.4     .12       0
   310.8    .045       0   336.2     .12       0
Bank Sta=310.8,336.2
XS Rating Curve= 0 ,0
Exp/Cntr=0.3,0.1

Type RM Length L Ch R = 1 ,1269.7  ,160.2,154,146.6
XS GIS Cut Line= 3
     2022011.253      183018.673     2022282.954      182878.916
     2022341.982      182796.451
#Sta/Elev= 30
       0 1672.71     6.5 1671.68     9.8 1670.23    16.2 1664.88    19.5 1663.76
    29.2 1664.57    35.8 1664.06      39 1662.84    48.8 1655.08    61.8 1646.08
    74.8 1636.35      91 1631.66     104 1630.38     130 1629.58     156 1630.51
   162.5 1631.33   165.8 1630.68   175.5 1626.87   183.5 1625.55   191.8 1624.89
   198.5  1625.3     208 1626.48   214.5 1628.21   224.3 1629.74   243.8 1631.06
   276.3 1637.64   348.1 1645.08   361.2 1647.26   377.5 1651.35     407 1656.83
#Mann= 5 ,-1 , 0
       0     .12       0    19.5    .016       0    61.8     .12       0
   183.5    .045       0   198.5     .12       0
Bank Sta=183.5,198.5
XS Rating Curve= 0 ,0
Exp/Cntr=0.3,0.1

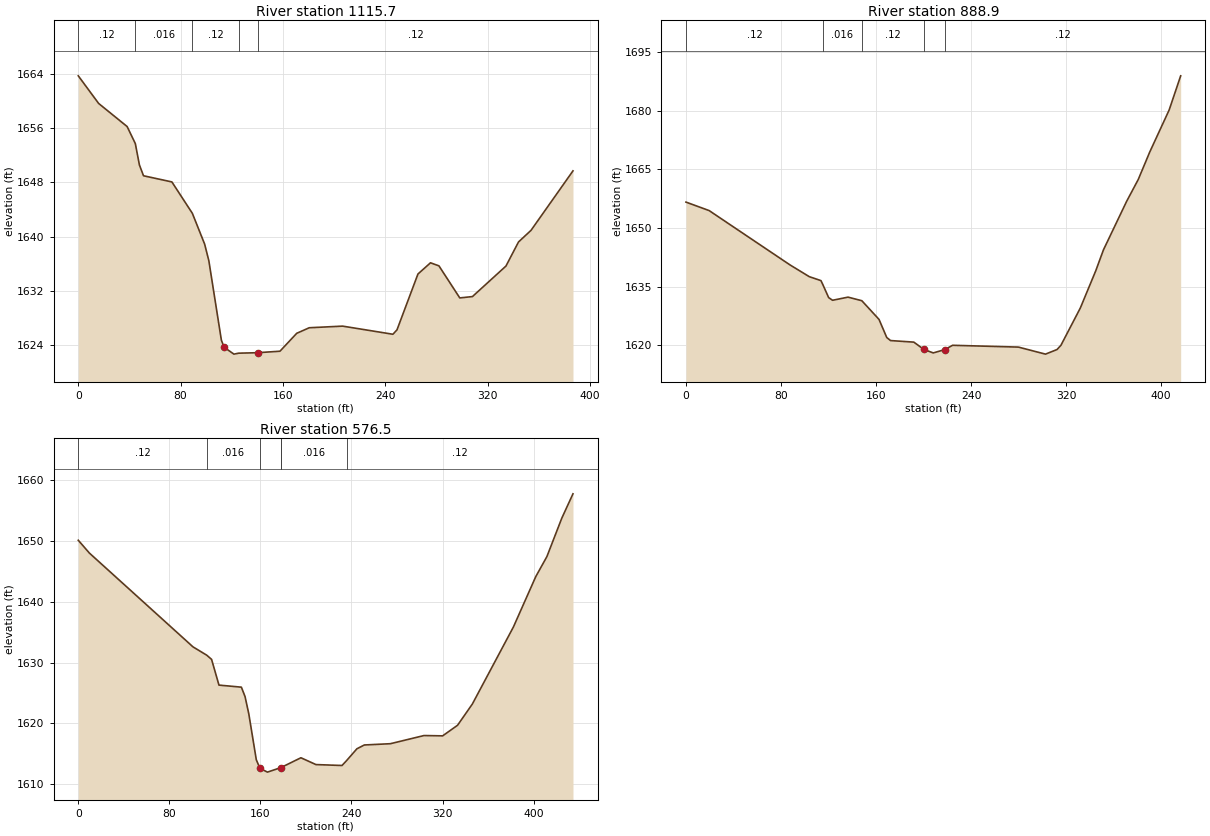
Type RM Length L Ch R = 1 ,1115.7  ,222.6,226.8,231.2
XS GIS Cut Line= 4
     2022103.266      183151.486     2022187.468      183106.347
     2022308.996      182987.423     2022368.023       182881.52
#Sta/Elev= 30
       0 1663.73    15.9 1659.66    38.2 1656.25    44.6 1653.74    47.8 1650.59
      51 1648.99    73.2 1648.08    89.2 1643.45    98.8 1638.91   102.1 1636.45
   111.9 1624.73  114.03 1623.69   121.7 1622.68   125.4 1622.82   140.4 1622.89
   157.7 1623.11   170.8 1625.75   180.6 1626.57   206.7 1626.81     246 1625.61
   249.2 1626.26   265.6  1634.5   275.4 1636.15     282  1635.7   298.3 1630.97
   308.2 1631.17   334.4 1635.67   344.2 1639.22     354 1640.94   386.8 1649.71
#Mann= 5 ,-1 , 0
       0     .12       0    44.6    .016       0    89.2     .12       0
   125.4    .045       0   140.4     .12       0
Bank Sta=114.03,140.4
XS Rating Curve= 0 ,0
Exp/Cntr=0.3,0.1

Type RM Length L Ch R = 1 ,888.9   ,315.7,312.4,306.6
XS GIS Cut Line= 4
     2022215.607      183295.424     2022309.357      183269.382
     2022508.576      183127.889     2022551.545      183066.691
#Sta/Elev= 30
       0 1656.65    19.5 1654.48    87.6 1640.57   103.8 1637.57   113.6 1636.56
  115.141635.583   120.1 1632.21   123.4 1631.53   136.4 1632.33  148.021631.417
   162.5 1626.63     169    1622   172.2 1621.22   191.8 1620.82   200.2 1618.96
   208.1 1618.06   217.8  1618.9   224.4 1620.01   279.8 1619.55   302.6 1617.75
   312.3 1618.92   315.6 1620.01   331.9 1629.53   344.9 1639.06   351.4 1644.43
   370.9 1656.84   380.7 1662.44   390.4 1669.49   406.7 1680.22   416.4 1688.96
#Mann= 5 ,-1 , 0
       0     .12       0  115.14    .016       0  148.02     .12       0
   200.2    .045       0   217.8     .12       0
Bank Sta=200.2,217.8
XS Rating Curve= 0 ,0
Exp/Cntr=0.3,0.1

Type RM Length L Ch R = 1 ,576.5   ,497.3,495.8,494.5
XS GIS Cut Line= 3
     2022361.441       183524.59     2022475.044      183496.292
     2022707.795      183280.233
#Sta/Elev= 30
       0  1650.1     9.8 1647.99   100.8 1632.58  112.881631.212   117.1 1630.53
   123.6  1626.3   143.3 1625.96   146.5 1624.42   149.8 1621.59   156.4 1614.03
   159.6 1612.62   166.2    1612   178.2 1612.76  178.341612.777   195.6 1614.36
   208.8 1613.24   231.7 1613.09  235.861613.924   244.8 1615.84   251.3 1616.46
   274.2 1616.67   303.7 1618.01   320.1 1617.96   333.2  1619.7   346.2 1623.19
   382.3 1635.86   401.9 1644.12   411.7 1647.42   424.8 1653.74   434.6 1657.73
#Mann= 6 ,-1 , 0
       0     .12       0  112.88    .016       0   159.6    .045       0
   178.2     .12       0  178.34    .016       0  235.86     .12       0
Bank Sta=159.6,178.2
XS Rating Curve= 0 ,0
Exp/Cntr=0.3,0.1