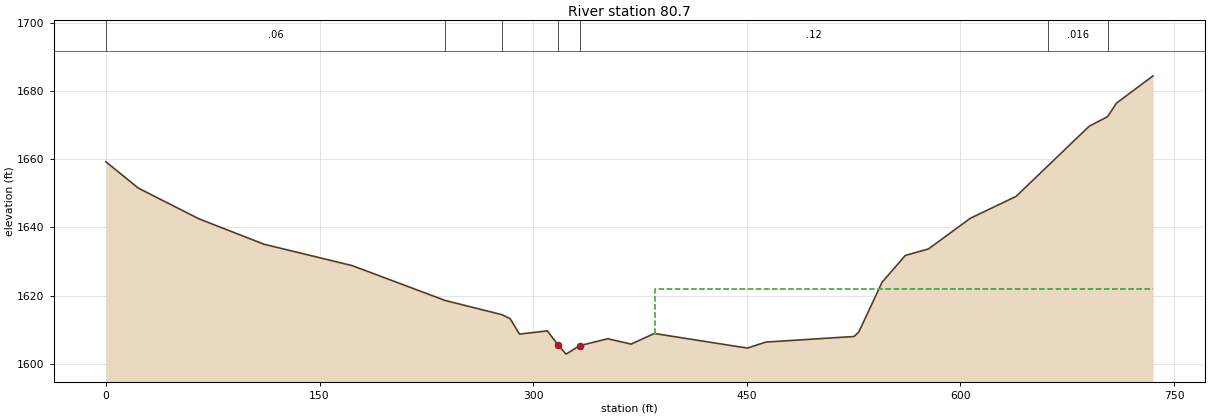
HEC-RAS study STNKLKCK.prj: STNKLKCK

--- STNKLKCK.g01 (geometry) --- (continued)

Type RM Length L Ch R = 1 ,80.7    ,93.5,80.7,66.3
XS GIS Cut Line= 3
     2022625.764      184071.899     2023024.201       183609.66
     2023149.201       183609.66
#Sta/Elev= 30
       0 1659.33    22.8 1651.57    65.3 1642.56     111 1635.08     173 1628.78
  238.421618.515  278.04 1614.37   283.9 1613.17   290.4 1608.66     310 1609.59
   317.6 1605.43   323.1 1602.76   332.6 1605.24   352.4 1607.29   368.8 1605.71
   385.1 1608.83   450.4 1604.54   463.4  1606.3   525.4 1607.95   528.7 1609.29
     545 1623.88   561.3 1631.77   577.6  1633.7     607 1642.71   639.1 1649.14
   661.5 1658.14   690.4 1669.76  703.441672.615   709.6 1676.57   735.3  1684.6
#Mann= 7 ,-1 , 0
       0     .06       0  238.42     .12       0  278.04    .016       0
   317.6    .045       0   332.6     .12       0   661.5    .016       0
  703.44     .12       0
#XS Ineff= 2 , 0
                          385.23         1622.04
Permanent Ineff=
       F       F
Bank Sta=317.6,332.6
XS Rating Curve= 0 ,0
Exp/Cntr=0.3,0.1

Chan Stop Cuts=-1
Use User Specified Reach Order=0
Composite Channel Slope=5